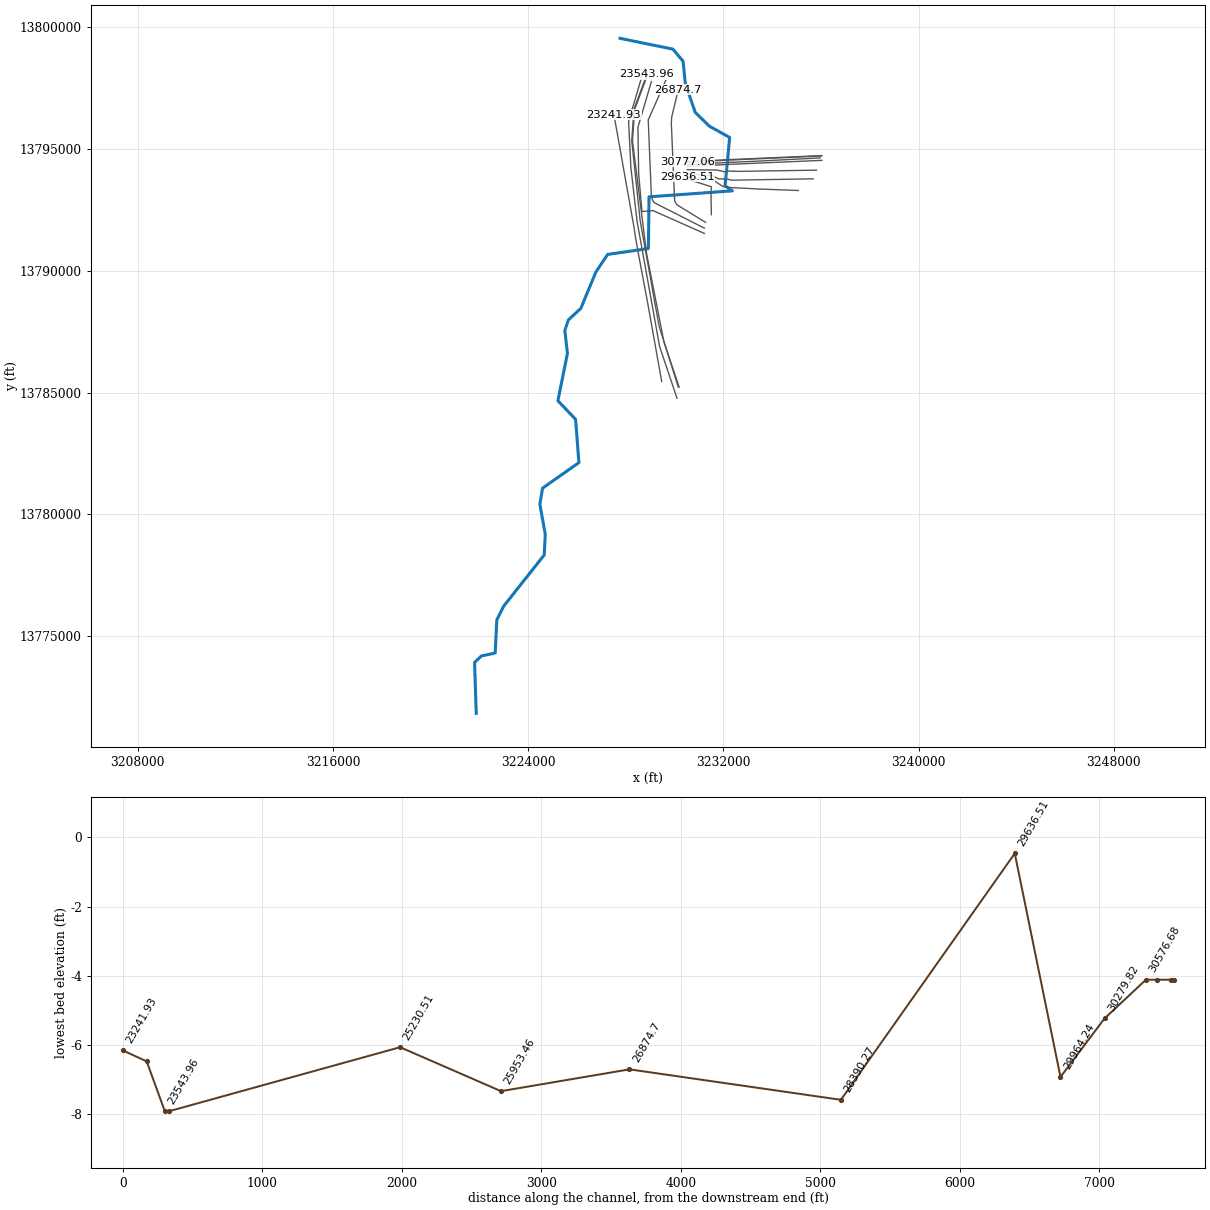
--- A104_00_00.prj (project) ---

Proj Title=A104-00-00
Current Plan=p01
Default Exp/Contr=.3,.1
English Units
Geom File=g01
Geom File=g02
Flow File=f02
Flow File=f01
Plan File=p01
Plan File=p02
Y Axis Title=Elevation
X Axis Title(PF)=Main Channel Distance
X Axis Title(XS)=Station
BEGIN DESCRIPTION:
Clear Creek Basin
Taylor Bayou
A104-00-00
Flood Hazard Model
10%, 2%, 1% and 0.2% Events
Filename: A104_00_00.prj
Prepared by: Perry Vaught	Date: 4-19-04
Reviewed by: __________	Date:
Status: (FINAL)
END DESCRIPTION:
DSS Export Rating Curves= 0
DSS Export Rating Curve Sorted= 0
DSS Export Volume Flow Curves= 0
DXF OffsetX= 0
DXF OffsetY= 0
DXF ScaleX= 1
DXF ScaleY= 10

--- A104_00_00.p01 (plan) ---

Plan Title=FEMA Effective June 2007
Version=Version 3.0.1  Mar 2001
Short Identifier=FEMAeff0607
Geom File=g01
Flow File=f01
Subcritical Flow
K Sum by GR= 0
Std Step Tol= 0.01
Critical Tol= 0.01
Num of Std Step Trials= 20
Max Error Tol= 0.3
Flow Tol Ratio= 0.001
Split Flow NTrial= 30
Split Flow Tol= 0.02
Split Flow Ratio= 0.02
Log Output Level= 0
Friction Slope Method= 0
Unsteady Friction Slope Method= 2
Secant Critical Depth
Global Vel Dist= 0 , 0 , 0
Global Log Level= 0
CheckData=True
Encroach Param= 0 ,0,0, 2
Computation Interval=1HOUR
Output Interval=1HOUR
Run HTab= 0
Run UNet= 0
Run PostProcess= 0
UNET Theta= 1
UNET ZTol= 0.02
UNET ZSATol= 0.1
UNET MxIter= 20
UNET MaxInSteps= 20
UNET DtIC= 0
UNET DtMin= 0
UNET MaxCRTS= 20
UNET WFStab= 2
UNET SFStab= 1
UNET WFX= 1
UNET SFX= 1
UNET Convert EG Bridges=-1
UNET Use Existing IB Tables=-1
Instantaneous Interval=1HOUR
Write IC File= 0
IC Time=0
Write Velocity= 0
Write Detailed= 0

--- A104_00_00.p02 (plan) ---

Plan Title=Floodway
Version=Version 3.0.1  Mar 2001
Short Identifier=Floodway0607
Geom File=g02
Flow File=f02
Subcritical Flow
K Sum by GR= 0
Std Step Tol= 0.01
Critical Tol= 0.01
Num of Std Step Trials= 20
Max Error Tol= 0.3
Flow Tol Ratio= 0.001
Split Flow NTrial= 30
Split Flow Tol= 0.02
Split Flow Ratio= 0.02
Log Output Level= 0
Friction Slope Method= 0
Unsteady Friction Slope Method= 2
Secant Critical Depth
Global Vel Dist= 0 , 0 , 0
Global Log Level= 0
CheckData=True
Encroach Param=-1 ,0,0, 2
Encroach River=A104-00-00
Encroach Reach=A104-00-00_0030
Encroach Node=30777.06
       1 4953.67 5046.33
Encroach Node=30756.12
       1 4953.67 5046.33
Encroach Node=30707
       1 4953.67 5046.33
Encroach Node=30658.05
       1 4953.67 5046.33
Encroach Node=30576.68
       1    4936 5038.92
Encroach Node=30279.82
       1 4944.46 5055.54
Encroach Node=29964.24
       1 4950.97 5049.03
Encroach Node=29636.51
       1 4879.31 5120.69
Encroach Node=28390.27
       1 4929.55 5070.45
Encroach Node=26874.7
       1 4927.88 5072.12
Encroach Node=25953.46
       1 4929.57 5070.43
Encroach Node=25230.51
       1 4936.51 5063.49
Encroach Node=23573.98
       1 4869.76 5130.24
Encroach Node=23543.96
       1 4869.76    5198
Encroach Node=23478
       1 4869.76 5130.24
Encroach Node=23413.87
       1 4871.07 5128.93
Encroach Node=23241.93
       1    4916    5068
Encroach Node=23228
       1 4953.88 5046.12
Encroach Node=23216.18
       1    4912    5061
Encroach Node=23133.07
       1    4641    4852
Encroach Node=22407.37
       1  4668.4 5390.08
Encroach Node=20816.67
       1 4617.51 5410.42
Encroach Node=19618.56
       1 4675.67 5316.54
Encroach Node=19598.26
       1    4658    5369
Encroach Node=19566
       1 4664.92 5335.08
Encroach Node=19534.55
       1    4655    5336
Encroach Node=19486.95
       1    4650    5338
Encroach Node=19464.87
       1    4642    5340
Encroach Node=19441
       1 4688.94    5340
Encroach Node=19419.13
       1    4630    5340
Encroach Node=19325.73
       1    4620    5485
Encroach Node=17007.19
       1 4459.95 5540.05
Encroach Node=15331.72
       1  4503.4    5520
Encroach Node=14249.68
       1    4414 5472.95
Encroach Node=14213.73
       1 4527.05 5472.95
Encroach Node=14178
       1 4527.05 5472.95
Encroach Node=14143.7
       1 4527.05 5472.95
Encroach Node=14023.11
       1 4483.24 5472.95
Encroach Node=13273.42
       1    4555 5397.41
Encroach Node=11429.2
       1 4459.48 5540.52
Encroach Node=10155.22
       1 4070.52 5243.38
Encroach Node=9053.234
       1 4646.72 5353.29
Encroach Node=8149.993
       1  4392.3 5510.93
Encroach Node=7544.621
       1    4323    5926
Encroach Node=5194.954
       1 4222.43 5476.87
Encroach Node=3430.390
       1 4849.41    5093
Encroach Node=3237.425
       1 4879.01 5105.88
Encroach Node=3074.884
       1 4925.57    5100
Encroach Node=3043
       1    4915    5109
Encroach Node=3011.377
       1 4923.77    5100
Encroach Node=2970.952
       1    4866 5121.86
Computation Interval=1HOUR
Output Interval=1HOUR
Run HTab= 0
Run UNet= 0
Run PostProcess= 0
UNET Theta= 1
UNET ZTol= 0.02
UNET ZSATol= 0.1
UNET MxIter= 20
UNET MaxInSteps= 20
UNET DtIC= 0
UNET DtMin= 0
UNET MaxCRTS= 20
UNET WFStab= 2
UNET SFStab= 1
UNET WFX= 1
UNET SFX= 1
UNET Convert EG Bridges=-1
UNET Use Existing IB Tables=-1
Instantaneous Interval=1HOUR
Write IC File= 0
IC Time=0
Write Velocity= 0
Write Detailed= 0

--- A104_00_00.f01 (steady flow) ---

Flow Title=FEMA Effective June 2007
Version=Version 3.0.1  Mar 2001
Number of Profiles= 4
Profile Names=10PCT_10yr, 2PCT_50yr, 1PCT_100yr, 0.2PCT_500yr
River Rch & RM=A104-00-00,A104-00-00_0030      ,30777.06
     691    1057    1250    1818
River Rch & RM=A104-00-00,A104-00-00_0030      ,30576.68
     720    1101    1301    1893
River Rch & RM=A104-00-00,A104-00-00_0030      ,30279.82
     752    1150    1359    1977
River Rch & RM=A104-00-00,A104-00-00_0030      ,29964.24
     786    1203    1421    2068
River Rch & RM=A104-00-00,A104-00-00_0030      ,29636.51
     786    1203    1421    2068
River Rch & RM=A104-00-00,A104-00-00_0030      ,28390.27
       4       4       5       5
River Rch & RM=A104-00-00,A104-00-00_0030      ,26874.7
       8      11      12      15
River Rch & RM=A104-00-00,A104-00-00_0030      ,25953.46
      15      22      25      33
River Rch & RM=A104-00-00,A104-00-00_0030      ,25230.51
      63     108     132     206
River Rch & RM=A104-00-00,A104-00-00_0030      ,23573.98
      65     111     136     213
River Rch & RM=A104-00-00,A104-00-00_0030      ,23543.96
      73     126     155     246
River Rch & RM=A104-00-00,A104-00-00_0030      ,23413.87
      84     149     185     298
River Rch & RM=A104-00-00,A104-00-00_0030      ,23241.93
      86     153     189     306
River Rch & RM=A104-00-00,A104-00-00_0030      ,23216.18
      92     166     206     336
River Rch & RM=A104-00-00,A104-00-00_0030      ,23133.07
     820    1290    1539    2291
River Rch & RM=A104-00-00,A104-00-00_0030      ,19419.13
    1751    2952    3604    5439
River Rch & RM=A104-00-00,A104-00-00_0030      ,17007.19
    2668    4469    5386    8051
River Rch & RM=A104-00-00,A104-00-00_0030      ,15331.72
    2768    4671    5619    8384
River Rch & RM=A104-00-00,A104-00-00_0030      ,14213.73
    2578    4777    5833    8843
River Rch & RM=A104-00-00,A104-00-00_0030      ,11429.2
    2427    4870    6021    9254
River Rch & RM=A104-00-00,A104-00-00_0030      ,9053.234
    2335    4929    6144    9524
River Rch & RM=A104-00-00,A104-00-00_0030      ,7544.621
    2200    5024    6340    9962
River Rch & RM=A104-00-00,A104-00-00_0030      ,5194.954
    2078    5115    6532   10394
Boundary for River Rch & Prof#=A104-00-00,A104-00-00_0030      , 1
Up Type= 0
Dn Type= 1
Dn Known WS=.9
Boundary for River Rch & Prof#=A104-00-00,A104-00-00_0030      , 2
Up Type= 0
Dn Type= 1
Dn Known WS=1.3
Boundary for River Rch & Prof#=A104-00-00,A104-00-00_0030      , 3
Up Type= 0
Dn Type= 1
Dn Known WS=1.45
Boundary for River Rch & Prof#=A104-00-00,A104-00-00_0030      , 4
Up Type= 0
Dn Type= 1
Dn Known WS=1.75
DSS Import GetInterval= 0
DSS Import GetPeak= 0
DSS Import FillOption= 0

--- A104_00_00.f02 (steady flow) ---

Flow Title=Floodway
Version=Version 3.0.1  Mar 2001
Number of Profiles= 2
Profile Names=1PCT_100yr, 1PCTFloodway_100yrFW
River Rch & RM=A104-00-00,A104-00-00_0030      ,30777.06
    1250    1250
River Rch & RM=A104-00-00,A104-00-00_0030      ,30576.68
    1301    1301
River Rch & RM=A104-00-00,A104-00-00_0030      ,30279.82
    1359    1359
River Rch & RM=A104-00-00,A104-00-00_0030      ,29964.24
    1421    1421
River Rch & RM=A104-00-00,A104-00-00_0030      ,29636.51
    1421    1421
River Rch & RM=A104-00-00,A104-00-00_0030      ,28390.27
       5       5
River Rch & RM=A104-00-00,A104-00-00_0030      ,26874.7
      12      12
River Rch & RM=A104-00-00,A104-00-00_0030      ,25953.46
      25      25
River Rch & RM=A104-00-00,A104-00-00_0030      ,25230.51
     132     132
River Rch & RM=A104-00-00,A104-00-00_0030      ,23573.98
     136     136
River Rch & RM=A104-00-00,A104-00-00_0030      ,23543.96
     155     155
River Rch & RM=A104-00-00,A104-00-00_0030      ,23413.87
     185     185
River Rch & RM=A104-00-00,A104-00-00_0030      ,23241.93
     189     189
River Rch & RM=A104-00-00,A104-00-00_0030      ,23216.18
     206     206
River Rch & RM=A104-00-00,A104-00-00_0030      ,23133.07
    1539    1539
River Rch & RM=A104-00-00,A104-00-00_0030      ,19419.13
    3604    3604
River Rch & RM=A104-00-00,A104-00-00_0030      ,17007.19
    5386    5386
River Rch & RM=A104-00-00,A104-00-00_0030      ,15331.72
    5619    5619
River Rch & RM=A104-00-00,A104-00-00_0030      ,14213.73
    5833    5833
River Rch & RM=A104-00-00,A104-00-00_0030      ,11429.2
    6021    6021
River Rch & RM=A104-00-00,A104-00-00_0030      ,9053.234
    6144    6144
River Rch & RM=A104-00-00,A104-00-00_0030      ,7544.621
    6340    6340
River Rch & RM=A104-00-00,A104-00-00_0030      ,5194.954
    6532    6532
Boundary for River Rch & Prof#=A104-00-00,A104-00-00_0030      , 1
Up Type= 0
Dn Type= 1
Dn Known WS=1.45
Boundary for River Rch & Prof#=A104-00-00,A104-00-00_0030      , 2
Up Type= 0
Dn Type= 1
Dn Known WS=2.45
DSS Import GetInterval= 0
DSS Import GetPeak= 0
DSS Import FillOption= 0

--- A104_00_00.g01 (geometry) ---

Geom Title=A104-00-00 June 2007
Version=Version 3.0.1  Mar 2001

River Reach=A104-00-00    ,A104-00-00_0030
Reach XY= 30
      3227766.75    13799516.999        3229932.       13799074.
        3230349.       13798578.      3230441.25       13797664.
        3230847.       13796483.        3231424.       13795918.
       3232258.5       13795454.      3232073.25       13793472.
      3232370.75       13793266.       3228954.5    13793020.999
      3228928.25       13790902.      3227260.75    13790660.999
        3226776.       13789939.       3226160.5    13788452.999
      3225646.75    13787972.999       3225502.5       13787540.
       3225610.5    13786604.999      3225218.25       13784664.
      3225943.25       13783899.        3226080.       13782126.
       3224589.5       13781079.       3224479.5       13780422.
      3224701.25       13779186.        3224657.       13778338.
       3223001.5    13776249.001        3222715.       13775682.
       3222648.5       13774322.       3222076.5       13774199.
      3221803.25       13773931.       3221871.5       13771848.

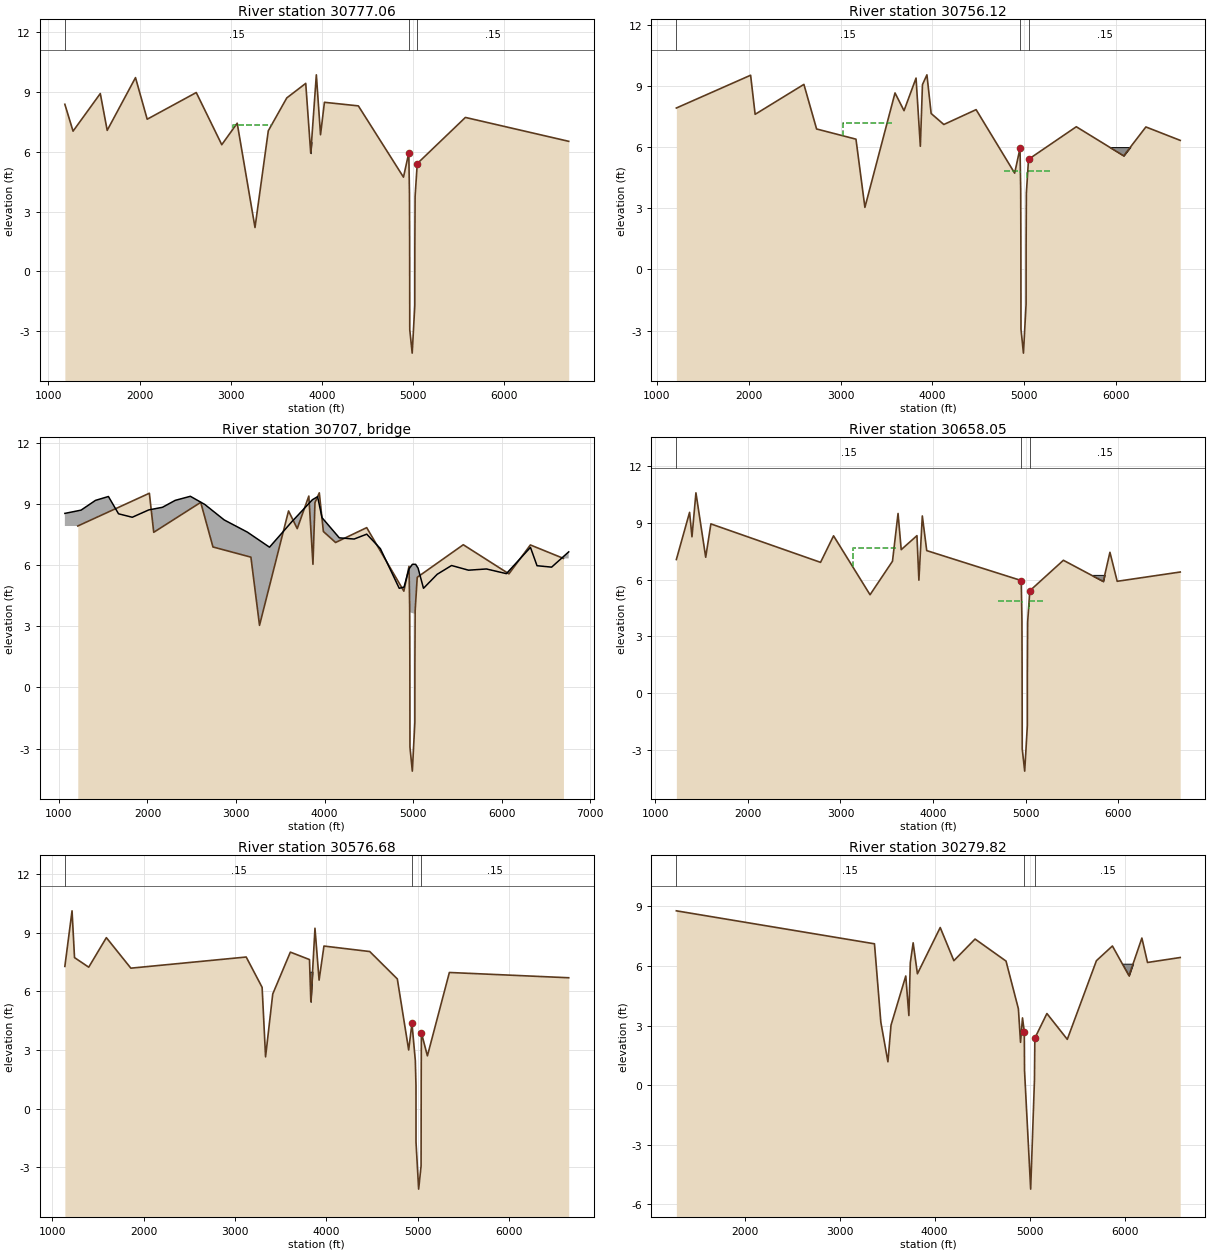
Type RM Length L Ch R = 1 ,30777.06,20.36,20.94,20.16
XS GIS Cut Line= 6
      3236044.48    13794710.551     3232436.968    13794555.186
     3232177.907    13794547.831     3231982.251    13794533.156
      3231301.17     13794498.98     3230523.691    13794464.075
#Sta/Elev= 30
 1181.24    8.39 1271.21    7.04 1569.96    8.93 1645.67    7.08 1956.12    9.73
 2084.29    7.64 2622.45    8.98  2902.3    6.36 3071.52    7.44 3266.84     2.2
 3412.76    7.06 3615.29    8.71 3823.24    9.44 3878.18    5.93 3939.57    9.87
 3985.58    6.86 4028.31    8.49 4400.36    8.31 4895.33    4.73 4953.67    5.95
 4961.08    3.88 4962.95    1.39 4964.23   -2.93 4990.88   -4.11 5019.61   -1.71
 5019.93    1.16 5022.85    3.76 5046.33    5.41 5574.57    7.73 6707.67    6.53
#Mann= 3 ,-1 , 0
 1181.24     .15       0 4953.67    .035       0 5046.33     .15       0
#XS Ineff= 1 ,-1
    3030    3452    7.35
Permanent Ineff=
       F
#Block Obstruct= 2 ,-1
    5870    6720     6.5    3835    3920     6.5
Bank Sta=4953.67,5046.33
XS Rating Curve= 0
Exp/Cntr=.5,.3

Type RM Length L Ch R = 1 ,30756.12,96.69,98.07,95.77
XS GIS Cut Line= 6
     3236003.091    13794692.813     3232437.753    13794535.201
     3232178.878    13794527.847       3231983.5    13794513.194
     3231302.119    13794479.003     3230524.588    13794444.095
#Sta/Elev= 30
 1213.11    7.93 2021.28    9.54  2070.5    7.62  2601.2    9.09 2739.52     6.9
    3168     6.4  3265.3    3.05 3593.09    8.67 3691.15     7.8 3822.01     9.4
 3868.79    6.05 3891.79    9.08 3940.42    9.56 3986.43    7.66 4124.35    7.12
 4475.69    7.85 4895.33    4.73 4953.67    5.95 4961.08    3.88 4962.95    1.39
 4964.23   -2.93 4990.88   -4.11 5019.61   -1.71 5019.93    1.16 5022.85    3.76
 5046.33    5.41 5566.27    7.01 6082.03    5.58 6323.88       7 6697.39    6.34
#Mann= 3 ,-1 , 0
 1213.11     .15       0 4953.67    .035       0 5046.33     .15       0
#XS Ineff= 3 ,-1
    3023    3560    7.17    4775    4958    4.85    5033    5300    4.85
Permanent Ineff=
       F       F       F
#Block Obstruct= 2 ,-1
    5900    6700    6.01    5615    5700    6.15
Bank Sta=4953.67,5046.33
XS Rating Curve= 0
Exp/Cntr=.5,.3

Type RM Length L Ch R = 3 ,30707   ,,,
BEGIN DESCRIPTION:
SHOREACRES BLVD
END DESCRIPTION:
Bridge Culvert--1,0,-1,-1, 0
Deck Dist Width WeirC Skew NumUp NumDn MinLoCord MaxHiCord MaxSubmerge Is_Ogee
10,80,2.6,0, 38, 38, , , .95, 0, 0,0,,
    1067    1250    1413    1559    1673    1828    2014    2169    2313    2484
    2647    2866    3128    3378    3628    3862    3921    3971    4166    4334
    4476    4630    4843    4897    4954    4992    5028    5056    5117    5272
    5434    5625    5828    6053    6325    6399    6564    6757
    8.55    8.71    9.19    9.38    8.53    8.36    8.72    8.85    9.19    9.39
    8.99    8.23    7.63    6.89    8.13    9.22    9.37    8.34    7.35    7.29
    7.53    6.82    4.87    4.93    5.83    6.05    6.05    5.86    4.87    5.56
    5.99    5.76    5.82    5.59    6.88    5.98    5.91    6.66
                                                                                
                                                                                
                                    3.71    3.65    3.61
                                                                
    1067    1250    1413    1559    1673    1828    2014    2169    2313    2484
    2647    2866    3128    3378    3628    3862    3921    3971    4166    4334
    4476    4630    4843    4897    4954    4992    5028    5056    5117    5272
    5434    5625    5828    6053    6325    6399    6564    6757
    8.55    8.71    9.19    9.38    8.53    8.36    8.72    8.85    9.19    9.39
    8.99    8.23    7.63    6.89    8.13    9.22    9.37    8.34    7.35    7.29
    7.53    6.82    4.87    4.93    5.83    6.05    6.05    5.86    4.87    5.56
    5.99    5.76    5.82    5.59    6.88    5.98    5.91    6.66
                                                                                
                                                                                
                                    3.71    3.65    3.61
                                                                
BR Coef=-1 , 0 , 0 ,, 0 ,,,.8,0,,0,
WSPro=,,,, 1 ,,,, 0 ,,,, 0 ,,,,-1 ,-1 ,-1 , 0 , 0 , 0 , 0 , 0
BC Design=,, 0 ,, 0 ,,,,,,

Type RM Length L Ch R = 1 ,30658.05,81.28,81.38,80.65
XS GIS Cut Line= 6
     3235967.615    13794615.948       3233501.7    13794487.561
      3232441.48    13794440.272     3232183.489    13794432.926
     3231989.434    13794418.372     3230528.849    13794349.191
#Sta/Elev= 30
  1226.3    7.06 1369.14    9.55 1394.99    8.26 1437.82   10.58 1543.43    7.18
 1599.39    8.94 2784.55    6.91 2925.21    8.31 3319.54     5.2 3562.11    6.97
 3622.21    9.49 3656.43    7.58 3826.46    8.32 3847.42    5.97 3884.41    9.36
 3932.19    7.53 4953.67    5.95 4961.08    3.88 4962.95    1.39 4964.23   -2.93
 4990.88   -4.11 5019.61   -1.71 5019.93    1.16 5022.85    3.76 5046.33    5.41
 5409.25    7.02 5840.06     5.9 5912.19    7.44 5990.77    5.91 6671.76     6.4
#Mann= 3 ,-1 , 0
  1226.3     .15       0 4953.67    .035       0 5046.33     .15       0
#XS Ineff= 3 ,-1
    3131    3603    7.67    4700    4958    4.85    5033    5200    4.85
Permanent Ineff=
       F       F       F
#Block Obstruct= 1 ,-1
    5725    5890    6.25
Bank Sta=4953.67,5046.33
XS Rating Curve= 0
Exp/Cntr=.5,.3

Type RM Length L Ch R = 1 ,30576.68,291.63,296.86,233.02
XS GIS Cut Line= 6
     3236038.568    13794515.432     3232444.618    13794360.332
     3232187.372    13794352.993     3231994.431    13794338.522
     3231310.429      13794304.2     3230532.437    13794269.271
#Sta/Elev= 30
    1139    7.27 1217.67   10.11 1244.65    7.72 1400.13    7.23 1593.01    8.74
 1860.92    7.18  3122.7    7.75 3296.89     6.2 3334.59    2.65 3413.06    5.86
 3605.74       8 3815.02    7.62 3830.03    5.46 3875.07    9.22 3920.11    6.57
 3973.37    8.31 4474.18    8.03 4775.88    6.63    4900       3    4936    4.36
    4973    2.45 4980.07    1.16 4980.39   -1.71 5009.12   -4.11 5035.77   -2.93
 5037.05    1.39 5038.92    3.88    5105     2.7 5345.32    6.96 6650.77    6.69
#Mann= 3 ,-1 , 0
    1139     .15       0    4936    .035       0 5038.92     .15       0
#XS Ineff= 1 ,-1
    3109    3606    7.72
Permanent Ineff=
       F
#Block Obstruct= 2 ,-1
    3799    3858       7    5650    5760     6.4
Bank Sta=4936,5038.92
XS Rating Curve= 0
Exp/Cntr=.3,.1

Type RM Length L Ch R = 1 ,30279.82,370.99,315.58,330.51
XS GIS Cut Line= 6
     3235813.885    13794113.369     3232604.224    13794063.483
     3232148.709    13794079.394     3232046.548    13794047.807
     3231744.903    13794118.416     3230520.664    13794134.112
#Sta/Elev= 30
 1279.65    8.78 3366.39    7.12  3433.5    3.17 3508.03    1.18 3540.56    3.02
 3696.06     5.5 3728.71    3.51 3743.72    6.16 3773.74    7.17 3818.77    5.61
 4058.94    7.94 4202.65    6.27 4426.03    7.36 4752.01    6.25 4882.24    3.85
  4904.9    2.16 4925.45    3.39 4944.46     2.7 4947.01     .73 5011.61   -5.23
 5051.61     .27 5055.54    2.37 5182.63    3.61 5397.46    2.31 5704.26    6.27
 5872.49    7.01 6047.26    5.51 6183.06    7.41 6242.25    6.18 6586.85    6.43
#Mann= 3 ,-1 , 0
 1279.65     .15       0 4944.46    .035       0 5055.54     .15       0
#XS Ineff= 1 ,-1
    3352    3980    6.82
Permanent Ineff=
       F
#Block Obstruct= 1 ,-1
    5946    6120    6.12
Bank Sta=4944.46,5055.54
XS Rating Curve= 0
Exp/Cntr=.3,.1

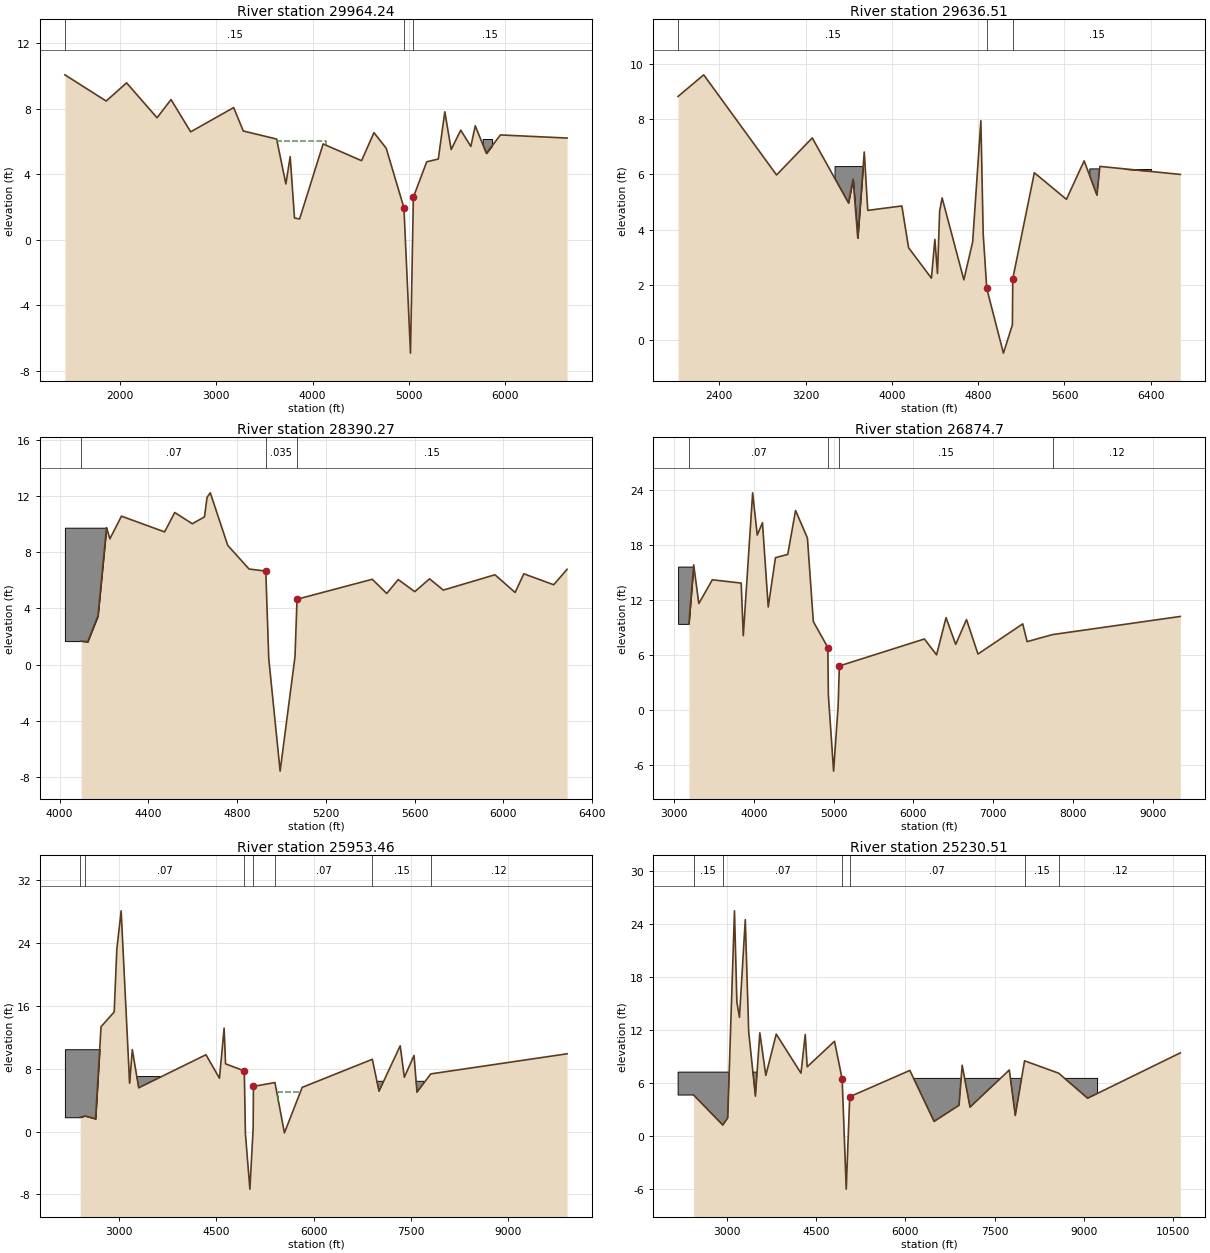
Type RM Length L Ch R = 1 ,29964.24,484.26,327.72,160.45
XS GIS Cut Line= 6
     3235677.893    13793758.607     3232309.936    13793702.489
      3232163.89    13793756.412     3231807.684    13793753.499
     3231564.406    13793882.986     3230501.045    13793973.234
#Sta/Elev= 30
 1424.74   10.07  1854.3    8.47 2066.31    9.58 2383.01    7.45 2528.69    8.56
 2732.82    6.59 3180.04    8.07 3280.21    6.64 3626.72    6.15 3722.93    3.41
 3767.94    5.07 3812.95    1.33  3865.8    1.27 4110.49    5.85 4510.21    4.83
 4639.22    6.54 4766.48    5.59 4950.97    1.95 5019.18   -6.92 5049.03     2.6
 5187.85    4.76 5308.21    4.93 5376.18    7.81 5442.33    5.51 5541.72    6.69
 5647.21     5.7 5692.47    6.96 5808.22    5.28 5954.92     6.4 6647.91    6.21
#Mann= 3 ,-1 , 0
 1424.74     .15       0 4950.97    .035       0 5049.03     .15       0
#XS Ineff= 1 ,-1
 3624.55 4144.55       6
Permanent Ineff=
       F
#Block Obstruct= 1 ,-1
    5770    5868    6.15
Bank Sta=4950.97,5049.03
XS Rating Curve= 0
Exp/Cntr=.3,.1

Type RM Length L Ch R = 1 ,29636.51,1696.75,1246.24,316.23
XS GIS Cut Line= 6
     3235074.798    13793279.678     3233425.568      13793341.8
     3232216.102    13793405.597     3231978.433     13793447.79
     3231552.634    13793722.109     3230512.817    13793847.672
#Sta/Elev= 30
 2017.23    8.82 2254.61     9.6 2930.13    5.98 3261.27    7.32 3596.74    4.97
 3639.67    5.83 3683.25     3.7 3743.31    6.81 3775.96     4.7 4091.93    4.86
 4154.57    3.35 4366.21    2.25 4398.27    3.65  4422.5    2.42 4442.49    4.67
 4465.51    5.15 4667.07    2.19 4748.59    3.56 4824.84    7.94  4846.4    3.85
 4879.31    1.88 5033.73    -.46 5117.02     .56 5120.69    2.23 5320.73    6.06
 5618.38     5.1  5782.4    6.49 5901.45    5.25 5928.27    6.29 6674.17       6
#Mann= 3 ,-1 , 0
 2017.23     .15       0 4879.31    .035       0 5120.69     .15       0
#XS Ineff= 1 ,-1
    3745    4816    6.24
Permanent Ineff=
       F
#Block Obstruct= 2 ,-1
    3468    3740     6.3    5835    6400     6.2
Bank Sta=4879.31,5120.69
XS Rating Curve= 0
Exp/Cntr=.3,.1

Type RM Length L Ch R = 1 ,28390.27,1503.36,1515.57,1452.12
XS GIS Cut Line= 6
     3231509.472    13792285.983     3231497.701    13792862.788
     3231495.508    13793117.497     3231499.929    13793258.335
     3231510.696     13793434.29     3230516.741    13793745.652
#Sta/Elev= 30
 4097.55    1.67  4126.5    1.62 4172.95    3.47 4211.54    9.75 4226.71    8.95
 4278.78   10.56 4473.35    9.44  4519.1   10.82 4598.32   10.02 4653.05   10.51
 4664.77    11.9  4679.4   12.22 4758.05    8.48 4854.15     6.8 4929.55    6.65
 4942.95     .43 4994.16   -7.58 5061.19     .56 5070.45    4.65 5409.58    6.07
 5474.88    5.06 5526.58    6.05 5601.36    5.19 5668.02     6.1 5729.92     5.3
 5962.79    6.39 6053.71    5.13 6092.93    6.46  6227.6    5.68 6287.97    6.78
#Mann= 3 ,-1 , 0
 4097.55     .07       0 4929.55    .035       0 5070.45     .15       0
#Block Obstruct= 1 ,-1
 4023.84 4211.56    9.74
Bank Sta=4929.55,5070.45
XS Rating Curve= 0
Exp/Cntr=.3,.1

Type RM Length L Ch R = 1 ,26874.7 ,800.64,921.25,895.33
XS GIS Cut Line= 6
     3231271.282    13791974.456     3230092.927    13792697.803
     3230004.181    13792853.268     3229868.056     13796049.58
     3229881.577    13796279.426     3230151.984    13797415.137
#Sta/Elev= 30
 3185.26    9.37 3245.47   15.81 3309.71   11.59 3478.95   14.18 3841.09   13.82
 3867.48    8.08  3984.7   23.67 4042.34   19.06 4107.91   20.41 4180.05   11.21
 4270.66   16.59 4424.72   16.95 4522.74   21.74 4671.66   18.74 4745.55    9.62
 4927.88    6.79 4933.98    1.65 4999.74    -6.7 5056.59     .39 5072.12    4.78
 6138.23    7.72 6290.96    5.99 6409.95   10.05 6530.61    7.13 6666.44    9.84
 6810.44    6.08 7371.69    9.37 7426.14    7.43 7745.23     8.2 9347.38   10.18
#Mann= 4 ,-1 , 0
 3185.26     .07       0 4927.88    .035       0 5072.12     .15       0
 7745.23     .12       0
#Block Obstruct= 1 ,-1
 3050.06 3241.95   15.62
Bank Sta=4927.88,5072.12
XS Rating Curve= 0
Exp/Cntr=.3,.1

Type RM Length L Ch R = 1 ,25953.46,329.82,722.95,574.61
XS GIS Cut Line= 6
     3231224.614    13791735.285     3229171.243    13792779.471
       3229098.8     13792877.75     3229046.684     13793120.37
      3228921.63    13796171.263      3229638.21    13797793.708
#Sta/Elev= 30
 2397.55    1.82 2472.66    1.99 2635.07    1.62 2719.82   13.35 2922.39   15.22
 2962.74   23.21 3029.84    28.1 3160.03    6.15 3201.74   10.43 3300.35    5.57
 4337.99    9.78 4546.02    6.79    4618   13.17 4640.14    8.62 4929.57    7.72
 4946.12    -.24 5015.47   -7.33 5065.61      .4 5070.43    5.75 5401.83    6.24
 5548.12    -.17 5821.74    5.62 6903.96     9.2 7007.13    5.14 7334.02   10.92
 7397.82    6.91 7547.28    9.69 7592.93    5.02 7805.25    7.34 9908.24     9.9
#Mann= 7 ,-1 , 0
 2397.55     .15       0 2472.66     .07       0 4929.57    .035       0
 5070.43     .15       0 5401.83     .07       0 6903.96     .15       0
 7805.25     .12       0
#XS Ineff= 1 ,-1
    5455    5810       5
Permanent Ineff=
       F
#Block Obstruct= 3 ,-1
  2162.1 2820.02   10.48    3110    3713       7    6189    7700     6.4
Bank Sta=4929.57,5070.43
XS Rating Curve= 0
Exp/Cntr=.3,.1

Type RM Length L Ch R = 1 ,25230.51,2402.42,1656.53,1378.71
XS GIS Cut Line= 6
     3231224.614    13791519.448     3229113.895    13792457.438
     3228664.805    13792415.047     3228528.828    13793978.528
     3228499.452    13795872.034     3229050.778    13797746.421
#Sta/Elev= 30
 2439.37    4.61 2930.23    1.21 3012.56    2.02  3126.2    25.5 3166.69   15.15
 3209.92   13.43 3308.03    24.5 3365.47   11.75 3478.32    4.49 3552.39   11.67
 3652.99    6.84 3828.11   11.52 4244.05    7.09  4315.7   11.47 4348.53    7.81
 4807.56   10.71 4936.51    6.42 5004.82   -6.06 5063.49    4.42 6073.95     7.4
 6481.85    1.62 6901.11    3.45 6953.52    7.99 7085.63    3.24 7746.15    7.45
 7846.45     2.3  8002.4    8.49 8575.06    7.09 9062.47    4.2510620.29    9.39
#Mann= 6 ,-1 , 0
 2439.37     .15       0 2930.23     .07       0 4936.51    .035       0
 5063.49     .07       0  8002.4     .15       0 8575.06     .12       0
#Block Obstruct= 2 ,-1
 2178.78    3555    7.21    6100    9230     6.5
Bank Sta=4936.51,5063.49
XS Rating Curve= 0
Exp/Cntr=.3,.1

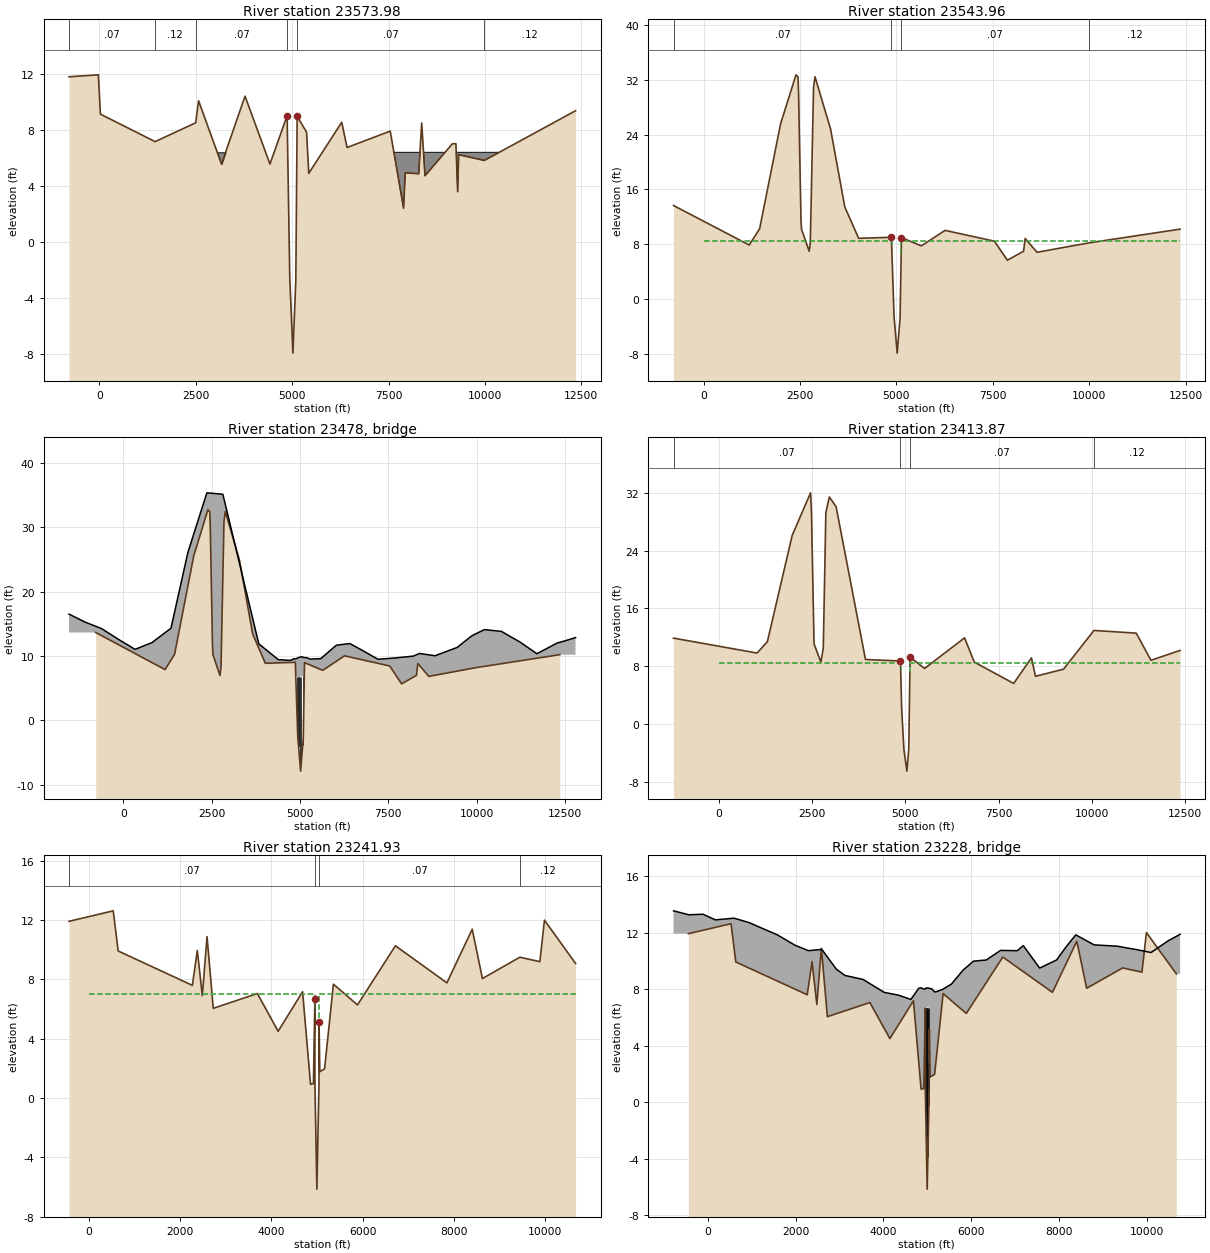
Type RM Length L Ch R = 1 ,23573.98,30.88,30.02,83.3
XS GIS Cut Line= 6
     3230189.362    13785220.193     3229566.018    13787072.415
      3228853.34    13790697.208     3228275.321    13795320.021
     3228364.246     13796603.93     3228895.411    13798026.582
#Sta/Elev= 30
 -787.16   11.78   -25.1   11.92   27.55    9.12 1446.26    7.16 2497.27     8.5
 2574.49   10.07 3168.27    5.56 3778.46    10.4 4424.94    5.56 4869.76    9.01
 4938.84   -2.55 5019.97   -7.91 5095.65   -2.72 5130.24    8.96 5374.66    7.83
 5431.24     4.9 6286.59    8.54 6424.37    6.74 7543.98    7.91 7889.66    2.42
 7934.23    4.94 8283.28    4.87 8360.13    8.49 8445.89    4.73 9157.27    7.01
 9247.48    7.01 9292.79    3.59 9318.38    6.23 9985.76    5.8212350.54    9.36
#Mann= 6 ,-1 , 0
 -787.16     .07       0 1446.26     .12       0 2497.27     .07       0
 4869.76    .035       0 5130.24     .07       0 9985.76     .12       0
#Block Obstruct= 2 ,-1
    7500   10500     6.4    2770    3600     6.4
Bank Sta=4869.76,5130.24
XS Rating Curve= 0
Exp/Cntr=.5,.3

Type RM Length L Ch R = 1 ,23543.96,137.6,130.1,131.99
XS GIS Cut Line= 6
     3230153.743    13785220.193     3229361.205    13787740.284
     3228590.592     13792044.98     3228245.479    13795316.922
     3228335.075    13796611.098     3228867.513    13798037.612
#Sta/Elev= 30
 -781.07   13.65 1182.48    7.88 1452.68   10.26 1996.16   25.59 2395.35   32.74
 2448.17   32.42 2462.49   30.06 2524.34   11.71 2537.97    10.2 2737.02    6.97
 2766.58    8.22 2850.97    30.9  2888.5   32.46 3291.59   24.84 3661.89   13.43
 4020.94    8.86 4869.76    9.01 4938.84   -2.55 5019.97   -7.91 5095.65   -2.72
 5130.24    8.96 5646.45    7.76 6262.54   10.02 7542.58    8.44 7878.49    5.66
 8299.22    6.98 8338.78    8.83 8647.19    6.82 9992.74    8.1912357.73    10.2
#Mann= 4 ,-1 , 0
 -781.07     .07       0 4869.76    .035       0 5130.24     .07       0
 9992.74     .12       0
#XS Ineff= 2 , 0
       0    4878    8.51    5123       0    8.51
Permanent Ineff=
       F       F
Bank Sta=4869.76,5130.24
XS Rating Curve= 0
Exp/Cntr=.5,.3

Type RM Length L Ch R = 3 ,23478   ,,,
BEGIN DESCRIPTION:
HWY 146
END DESCRIPTION:
Bridge Culvert--1,0,-1,-1, 0
Deck Dist Width WeirC Skew NumUp NumDn MinLoCord MaxHiCord MaxSubmerge Is_Ogee
1,125,2.6,0, 44, 44, , , .95, 0, 0,0,,
   -1537   -1084    -620    -142     333     812    1350    1828    2366    2818
    2942    3836    4389    4698 4750.23 4826.92 4880.35 4920.11 4960.39    5001
 5040.33 5080.38 5120.51 5179.65 5220.27    5289    5589    6031    6412    6753
    7208    7658    8211    8386    8823    9449    9867   10222   10704   11232
   11709   12289   12460   12803
   16.51   15.27   14.27    12.6   11.03   12.08   14.31   26.08   35.37   35.15
   32.34   11.88    9.43    9.32    9.34    9.58    9.53    9.64    9.76     9.8
    9.87    9.83    9.74    9.75    9.66    9.52    9.58   11.67   11.93   10.91
    9.49    9.67    9.98   10.39   10.03   11.32   13.14    14.1   13.82   12.16
   10.35   12.03   12.28   12.86
                                                                                
                                                     6.7    6.72    6.75    6.78
     6.8    6.83    6.86
                                                                                
                                
   -1537   -1084    -620    -142     333     812    1350    1828    2366    2818
    2942    3836    4389    4698 4750.23 4826.92 4880.35 4920.11 4960.39    5001
 5040.33 5080.38 5120.51 5179.65 5220.27    5289    5589    6031    6412    6753
    7208    7658    8211    8386    8823    9449    9867   10222   10704   11232
   11709   12289   12460   12803
   16.51   15.27   14.27    12.6   11.03   12.08   14.31   26.08   35.37   35.15
   32.34   11.88    9.43    9.32    9.34    9.58    9.53    9.64    9.76     9.8
    9.87    9.83    9.74    9.75    9.66    9.52    9.58   11.67   11.93   10.91
    9.49    9.67    9.98   10.39   10.03   11.32   13.14    14.1   13.82   12.16
   10.35   12.03   12.28   12.86
                                                                                
                                                     6.7    6.72    6.75    6.78
     6.8    6.83    6.86
                                                                                
                                
Pier Skew, UpSta & Num, DnSta & Num=  ,4920, 4 ,4920, 4 , 3 , 3 , 0 ,,
     1.3     1.3       2       2
     -10     4.7    4.71    6.71
     1.3     1.3       2       2
     -10     4.7    4.71    6.71
Pier Skew, UpSta & Num, DnSta & Num=  ,4960, 4 ,4960, 4 , 3 , 3 , 0 ,,
     1.3     1.3       2       2
     -10    4.75   4.751   6.751
     1.3     1.3       2       2
     -10    4.75   4.751   6.751
Pier Skew, UpSta & Num, DnSta & Num=  ,5001, 4 ,5001, 4 , 3 , 3 , 0 ,,
     1.3     1.3       2       2
     -10    4.78   4.781   6.781
     1.3     1.3       2       2
     -10    4.78   4.781   6.781
Pier Skew, UpSta & Num, DnSta & Num=  ,5040, 4 ,5040, 4 , 3 , 3 , 0 ,,
     1.3     1.3       2       2
     -10     4.8    4.81    6.81
     1.3     1.3       2       2
     -10     4.8    4.81    6.81
Pier Skew, UpSta & Num, DnSta & Num=  ,5080, 4 ,5080, 4 , 3 , 3 , 0 ,,
     1.3     1.3       2       2
     -10    4.83   4.831   6.831
     1.3     1.3       2       2
     -10    4.83   4.831   6.831
BR Coef=-1 , 1 , 0 ,1.25, 0 ,,,.8,0,2,0,
WSPro=,,,, 1 ,,,, 0 ,,,, 0 ,,,,-1 ,-1 ,-1 , 0 , 0 , 0 , 0 , 0
BC Design=,, 0 ,, 0 ,,,,,,

Type RM Length L Ch R = 1 ,23413.87,184.92,171.94,168.22
XS GIS Cut Line= 6
     3230100.313    13784766.042      3229387.92    13786885.412
     3228462.072    13792025.145     3228210.339    13794221.265
     3228116.085    13796107.194     3228684.305    13798036.529
#Sta/Elev= 30
-1213.71    11.9 1025.25    9.84 1302.34   11.41 1967.85   26.08  2460.5   31.97
  2485.1   29.28 2553.68   11.12 2736.98    8.58  2801.9   10.54 2870.63   29.26
 2964.62    31.4 3145.42   30.05  3933.2    8.95 4871.07    8.74 4902.11    2.28
 4963.68   -3.49 5043.27   -6.47 5093.74   -3.39 5128.93    9.29 5517.86    7.71
 6590.15   11.94 6850.58    8.59 7906.23    5.64 8382.32    9.17  8491.6    6.63
  9242.8    7.6110059.25   12.9611192.95   12.59 11587.2    8.8412368.17    10.2
#Mann= 4 ,-1 , 0
-1213.71     .07       0 4871.07    .035       0 5128.93     .07       0
10059.25     .12       0
#XS Ineff= 2 , 0
       0    4878    8.51    5123       0    8.51
Permanent Ineff=
       F       F
Bank Sta=4871.07,5128.93
XS Rating Curve= 0
Exp/Cntr=.5,.3

Type RM Length L Ch R = 1 ,23241.93,31.32,25.75,34.32
XS GIS Cut Line= 6
     3229473.581    13785448.603     3228921.745    13788543.545
     3228515.139    13790703.006      3228388.31    13791424.229
     3228342.878    13791744.141     3227515.224    13796393.382
#Sta/Elev= 30
 -442.76   11.92   528.2   12.63  637.18    9.92 2265.55     7.6 2374.02    9.95
 2483.86    6.91 2587.16   10.89 2724.05    6.05 3691.99    7.05 4148.05     4.5
 4684.39    7.17 4859.59     .92  4922.8     .97 4953.88    6.65 4955.01     .99
  4998.1   -6.15 5044.23      .9 5046.12    5.16 5062.44    1.77 5167.69    1.97
 5361.32    7.68 5889.52    6.28 6722.18   10.27  7852.5    7.77    8408   11.39
 8632.17    8.06 9453.18     9.5  9892.6     9.2 9993.78      1210676.27    9.08
#Mann= 4 ,-1 , 0
 -442.76     .07       0 4953.88    .035       0 5046.12     .07       0
 9453.18     .12       0
#XS Ineff= 2 , 0
       0    4949       7    5046       0       7
Permanent Ineff=
       F       F
Bank Sta=4953.88,5046.12
XS Rating Curve= 0
Exp/Cntr=.5,.3

Type RM Length L Ch R = 3 ,23228   ,,,
BEGIN DESCRIPTION:
RAILROAD DS OF HWY 146
END DESCRIPTION:
Bridge Culvert--1,0,-1,-1, 0
Deck Dist Width WeirC Skew NumUp NumDn MinLoCord MaxHiCord MaxSubmerge Is_Ogee
5,15,2.6,0, 49, 49, , , .95, 0, 0,0,,
    -782    -432    -112     173     597     947    1247    1579    1984    2293
    2597    2929    3124    3540    4019    4347    4626    4807 4860.33 4916.72
    4954  4968.3  4983.1 4997.66 5012.59 5027.19 5037.75 5041.24 5099.34 5166.08
 5208.13    5348    5548    5818    6053    6344    6669    7051    7188    7561
    7946    8168    8384    8803    9325    9780   10099   10485   10761
   13.54   13.26    13.3    12.9   13.02    12.7   12.29   11.85   11.11   10.72
   10.81    9.41    8.97    8.68    7.77    7.57    7.27    8.07    8.09    8.01
    8.01    8.07    8.09    8.07    8.07    8.08    8.06    8.05    8.03     7.8
    7.82    7.98    8.35    9.35    9.98   10.06   10.74   10.72   11.08    9.49
   10.06   11.01   11.84   11.13   11.04   10.79   10.59   11.41   11.88
                                                                                
                                                                                
     6.7     6.7     6.7     6.7     6.7     6.7     6.7
                                                                                
                                                                        
    -782    -432    -112     173     597     947    1247    1579    1984    2293
    2597    2929    3124    3540    4019    4347    4626    4807 4860.33 4916.72
    4954  4968.3  4983.1 4997.66 5012.59 5027.19 5037.75 5041.24 5099.34 5166.08
 5208.13    5348    5548    5818    6053    6344    6669    7051    7188    7561
    7946    8168    8384    8803    9325    9780   10099   10485   10761
   13.54   13.26    13.3    12.9   13.02    12.7   12.29   11.85   11.11   10.72
   10.81    9.41    8.97    8.68    7.77    7.57    7.27    8.07    8.09    8.01
    8.01    8.07    8.09    8.07    8.07    8.08    8.06    8.05    8.03     7.8
    7.82    7.98    8.35    9.35    9.98   10.06   10.74   10.72   11.08    9.49
   10.06   11.01   11.84   11.13   11.04   10.79   10.59   11.41   11.88
                                                                                
                                                                                
     6.7     6.7     6.7     6.7     6.7     6.7     6.7
                                                                                
                                                                        
Pier Skew, UpSta & Num, DnSta & Num=  ,4955, 2 ,4955, 2 , 0 , 0 , 0 ,,
    1.25    1.25
       0     6.7
    1.25    1.25
       0     6.7
Pier Skew, UpSta & Num, DnSta & Num=  ,4969, 2 ,4969, 2 , 0 , 0 , 0 ,,
    1.25    1.25
       0     6.7
    1.25    1.25
       0     6.7
Pier Skew, UpSta & Num, DnSta & Num=  ,4983, 2 ,4983, 2 , 0 , 0 , 0 ,,
    1.25    1.25
       0     6.7
    1.25    1.25
       0     6.7
Pier Skew, UpSta & Num, DnSta & Num=  ,4998, 2 ,4998, 2 , 0 , 0 , 0 ,,
    1.25    1.25
       0     6.7
    1.25    1.25
       0     6.7
Pier Skew, UpSta & Num, DnSta & Num=  ,5013, 2 ,5013, 2 , 0 , 0 , 0 ,,
    1.25    1.25
       0     6.7
    1.25    1.25
       0     6.7
Pier Skew, UpSta & Num, DnSta & Num=  ,5027, 2 ,5027, 2 , 0 , 0 , 0 ,,
    1.25    1.25
       0     6.7
    1.25    1.25
       0     6.7
Pier Skew, UpSta & Num, DnSta & Num=  ,5037, 2 ,5037, 2 , 0 , 0 , 0 ,,
    1.25    1.25
       0     6.7
    1.25    1.25
       0     6.7
BR Coef=-1 , 1 , 0 ,1.25, 0 ,,,.8,0,2,0,
WSPro=,,,, 1 ,,,, 0 ,,,, 0 ,,,,-1 ,-1 ,-1 , 0 , 0 , 0 , 0 , 0
BC Design=,, 0 ,, 0 ,,,,,,