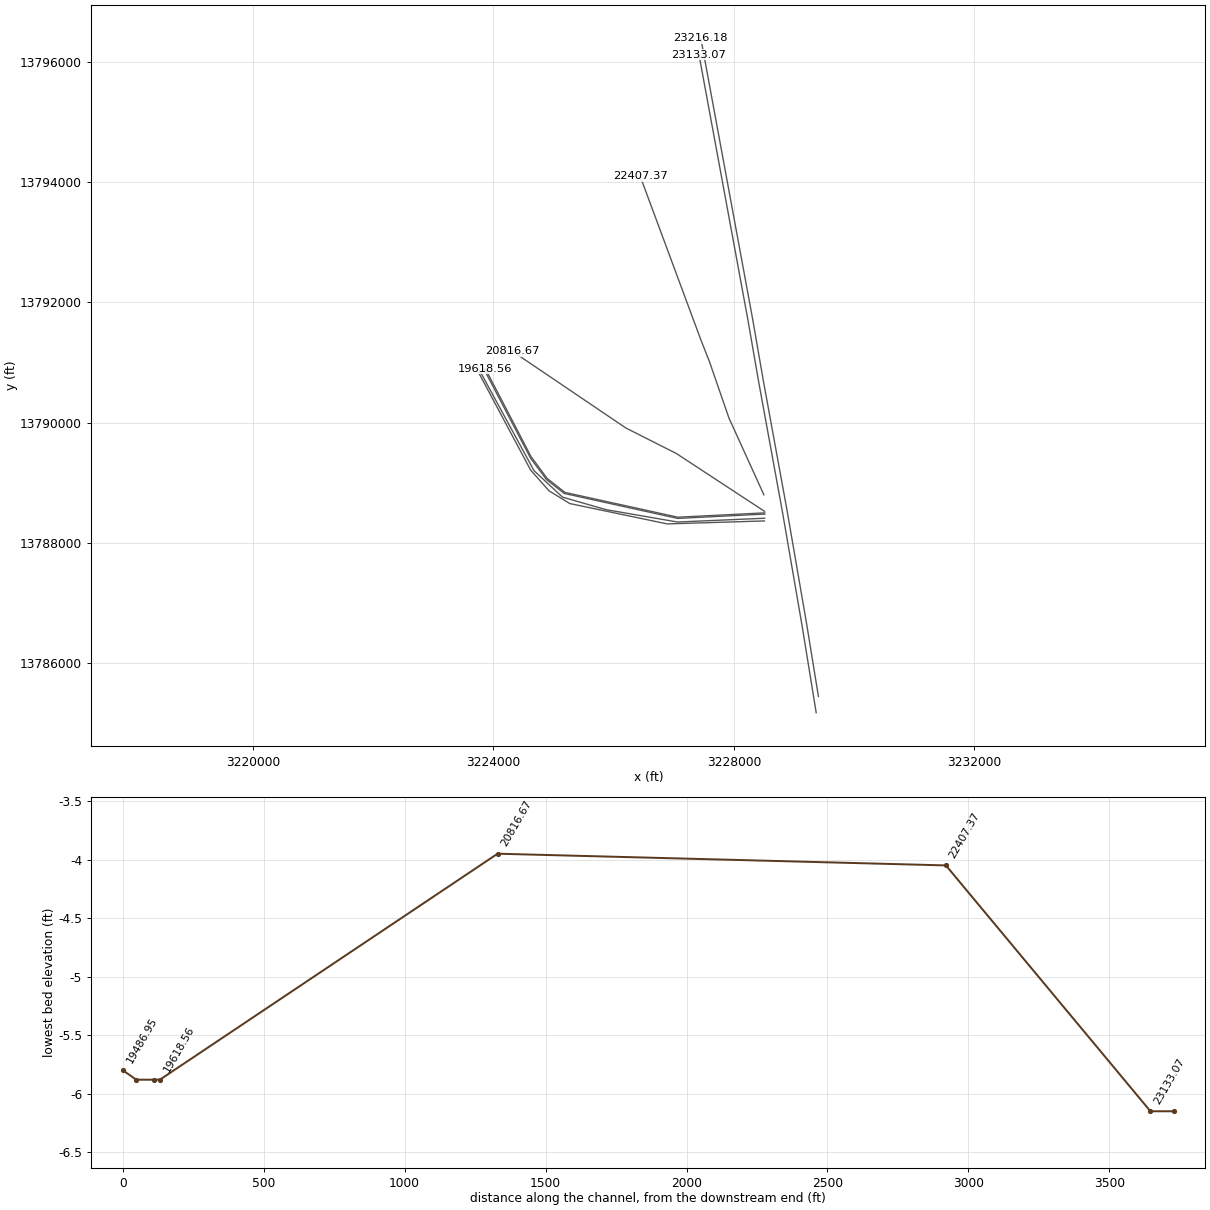
HEC-RAS study A104_00_00.prj: A104-00-00

--- A104_00_00.g01 (geometry) --- (continued)

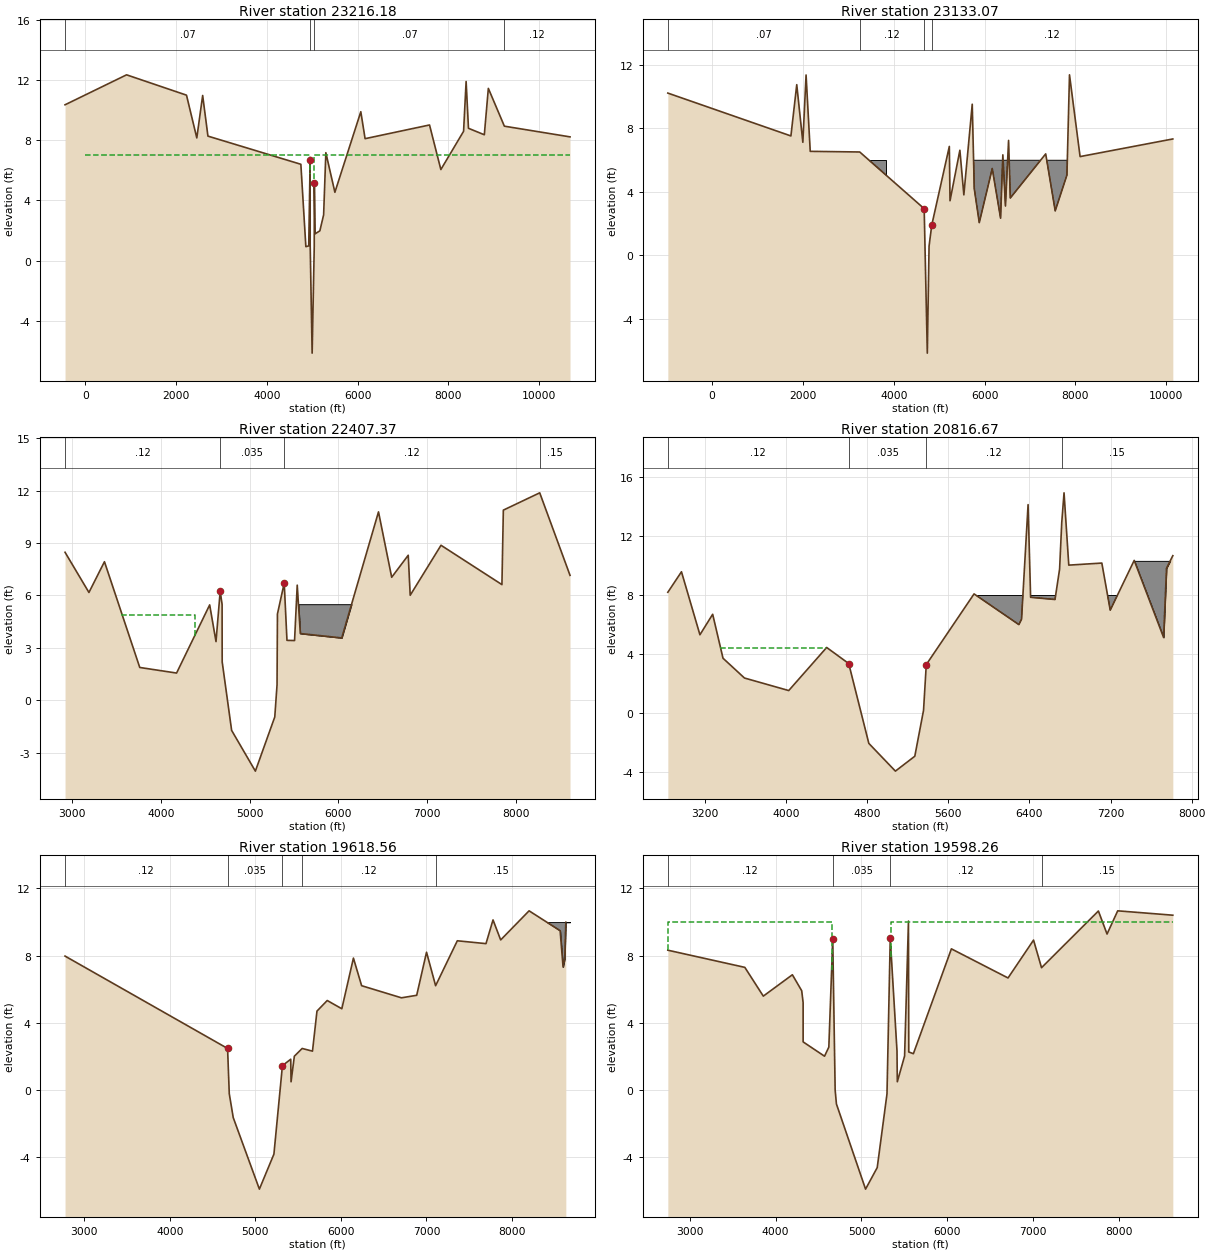
Type RM Length L Ch R = 1 ,23216.18,81.91,83.11,80.09
XS GIS Cut Line= 6
      3229407.53    13785442.259     3229212.038    13786645.754
     3228885.201    13788539.578     3228490.553    13790698.465
     3228309.995    13791738.062     3227451.165    13796391.444
#Sta/Elev= 30
 -444.68   10.34  910.66   12.33 2230.49   10.98 2457.56    8.14 2586.62   10.96
 2702.83    8.26 4749.63    6.39 4859.59     .92  4922.8     .97 4953.88    6.65
 4955.01     .99  4998.1   -6.15 5044.23      .9 5046.12    5.16 5062.44    1.77
 5167.69    1.97 5251.01    3.03 5299.91    7.16 5499.11    4.53  6069.9    9.88
 6164.26    8.09 7583.66       9 7833.18    6.04 8333.84    8.58 8389.46   11.89
 8441.34    8.78 8790.64    8.35 8879.13   11.43 9232.28    8.9210678.27    8.21
#Mann= 4 ,-1 , 0
 -444.68     .07       0 4953.88    .035       0 5046.12     .07       0
 9232.28     .12       0
#XS Ineff= 2 , 0
       0    4949       7    5046       0       7
Permanent Ineff=
       F       F
Bank Sta=4953.88,5046.12
XS Rating Curve= 0
Exp/Cntr=.5,.3

Type RM Length L Ch R = 1 ,23133.07,625.53,725.7,923.14
XS GIS Cut Line= 6
 3229370.252224713785172.7967296     3229133.139    13786632.521
     3228806.456    13788525.447     3228411.765    13790684.587
     3228231.253    13791723.905 3227419.941970513796121.2125033
#Sta/Elev= 30
 -976.28   10.23 1734.22    7.53 1862.79   10.76 1996.96    7.13 2068.04   11.37
 2159.89    6.56 3249.77    6.52    4669    2.95  4738.1   -6.15  4776.6     .59
    4836    1.91 5223.13    6.87 5238.34    3.45 5455.39    6.63 5542.55    3.82
 5727.67    9.53 5772.14    4.21  5882.4    2.07 6168.36    5.48 6351.69    2.35
 6401.58    6.34 6459.04    3.12  6527.8    7.25 6565.71    3.62 7345.13     6.4
 7554.78    2.81 7813.19    5.07 7869.38   11.38 8102.55    6.2310144.89    7.34
#Mann= 4 ,-1 , 0
 -976.28     .07       0 3249.77     .12       0    4669    .035       0
    4836     .12       0
#Block Obstruct= 2 ,-1
    5740   10160       6    3420    3830       6
Bank Sta=4669,4836
XS Rating Curve= 0
Exp/Cntr=.3,.1

Type RM Length L Ch R = 1 ,22407.37,1088.16,1590.7,2292.51
XS GIS Cut Line= 6
     3228499.505    13788798.171     3227917.667    13790078.215
     3227822.457    13790353.266     3227594.831    13791011.915
     3227457.465    13791359.762     3226440.842    13794101.017
#Sta/Elev= 30
 2919.69    8.47 3189.07    6.17 3363.97    7.93 3761.83    1.88 4176.86    1.56
 4549.97    5.46 4621.22    3.36  4668.4    6.24 4689.81    5.49 4690.86     2.2
 4797.33   -1.72 5064.96   -4.05 5283.67    -.95 5309.14     .88  5313.7    4.94
 5390.08    6.71 5421.08    3.43 5506.64    3.42  5536.7    6.59 5571.51    3.82
 6038.61    3.57  6452.7   10.78 6601.38    7.04 6787.95     8.3 6810.07    6.01
 7157.23    8.87 7843.84    6.62 7859.84   10.88 8269.89   11.87 8611.39    7.15
#Mann= 4 ,-1 , 0
 2919.69     .12       0  4668.4    .035       0 5390.08     .12       0
 8269.89     .15       0
#XS Ineff= 1 ,-1
 3545.01 4379.49    4.86
Permanent Ineff=
       F
#Block Obstruct= 1 ,-1
    5538    6245     5.5
Bank Sta=4668.4,5390.08
XS Rating Curve= 0
Exp/Cntr=.3,.1

Type RM Length L Ch R = 1 ,20816.67,995.73,1198.11,1516.46
XS GIS Cut Line= 4
     3228510.084     13788523.12     3227043.276    13789485.026
      3226203.89    13789908.953     3224309.944    13791189.994
#Sta/Elev= 30
 2833.29    8.17 2967.81    9.56 3149.89    5.29 3275.55    6.68 3377.54     3.7
 3589.02    2.36 4025.85    1.51 4399.99    4.43 4617.51    3.34 4815.81   -2.07
 5077.96   -3.95  5269.3   -2.94 5355.44     .17 5382.49    3.27  5853.8    8.06
 6295.66    5.98 6321.99    6.34 6386.57   14.11 6411.53    7.83 6652.24    7.68
 6697.48    9.74 6718.43   12.87 6741.23   14.91 6788.03   10.01 7114.04   10.15
 7196.99    6.96 7433.35   10.33 7723.34    5.11  7752.1     9.8 7814.23   10.65
#Mann= 4 ,-1 , 0
 2833.29     .12       0 4617.51    .035       0 5382.49     .12       0
 6718.43     .15       0
#XS Ineff= 1 ,-1
    3350    4392    4.37
Permanent Ineff=
       F
#Block Obstruct= 2 ,-1
    5862    7400    7.95 7433.75 7945.52    10.3
Bank Sta=4617.51,5382.49
XS Rating Curve= 0
Exp/Cntr=.3,.1

Type RM Length L Ch R = 1 ,19618.56,20,20.31,20.08
XS GIS Cut Line= 6
     3228514.012    13788497.048     3227067.331    13788424.881
     3225188.801    13788837.887     3224895.302    13789069.129
     3224626.457    13789433.318     3223865.811    13790896.099
#Sta/Elev= 30
 2776.32    7.97 4675.67    2.48  4695.4    -.21 4741.81   -1.63 5047.34   -5.88
 5217.17    -3.8 5316.54    1.46 5413.61    1.84 5417.44      .5 5455.86    2.02
 5547.37    2.48 5667.78    2.32 5720.23     4.7 5840.11    5.33 6010.68    4.84
 6146.28    7.85 6242.06    6.21 6707.26    5.49 6885.64    5.64 7000.46     8.2
 7106.65    6.21  7360.2    8.88 7695.25    8.71 7777.44   10.12 7866.79    8.93
 8198.86   10.66 8561.65    9.48 8596.05    7.32 8615.32     7.8 8628.12    9.98
#Mann= 5 ,-1 , 0
 2776.32     .12       0 4675.67    .035       0 5316.54     .12       0
 5547.37     .12       0 7106.65     .15       0
#Block Obstruct= 2 ,-1
 8202.82 8292.02    9.94 8304.94 8677.26    9.99
Bank Sta=4675.67,5316.54
XS Rating Curve= 0
Exp/Cntr=.5,.3

Type RM Length L Ch R = 1 ,19598.26,72.09,63.71,76.78
XS GIS Cut Line= 6
     3228515.317     13788477.09     3227066.083    13788404.854
     3225178.919    13788820.211     3224880.945    13789054.978
     3224621.956    13789401.812     3223840.424    13790893.835
#Sta/Elev= 30
 2743.18    8.32 3640.44     7.3  3855.8    5.59 4194.56    6.86 4303.29    5.91
 4319.82     5.2 4319.82    2.87 4569.25    2.02 4619.36    2.56 4664.92    8.98
 4692.99     .01 4707.95    -.82 5047.34   -5.88 5183.38    -4.6 5297.06    -.22
 5335.08    9.03 5413.61    2.34 5417.44      .5 5502.28    2.03 5547.37   10.05
 5550.82    2.27  5604.9    2.17 6047.63     8.4 6707.61    6.67    7005    8.92
 7097.93    7.28 7760.69   10.65 7861.51    9.28  7985.8   10.66 8627.98    10.4
#Mann= 4 ,-1 , 0
 2743.18     .12       0 4664.92    .035       0 5335.08     .12       0
 7097.93     .15       0
#XS Ineff= 2 , 0
       0    4651      10    5348       0      10
Permanent Ineff=
       F       F
#Block Obstruct= 1 ,-1
  8294.3 8685.48   10.02
Bank Sta=4664.92,5335.08
XS Rating Curve= 0
Exp/Cntr=.5,.3

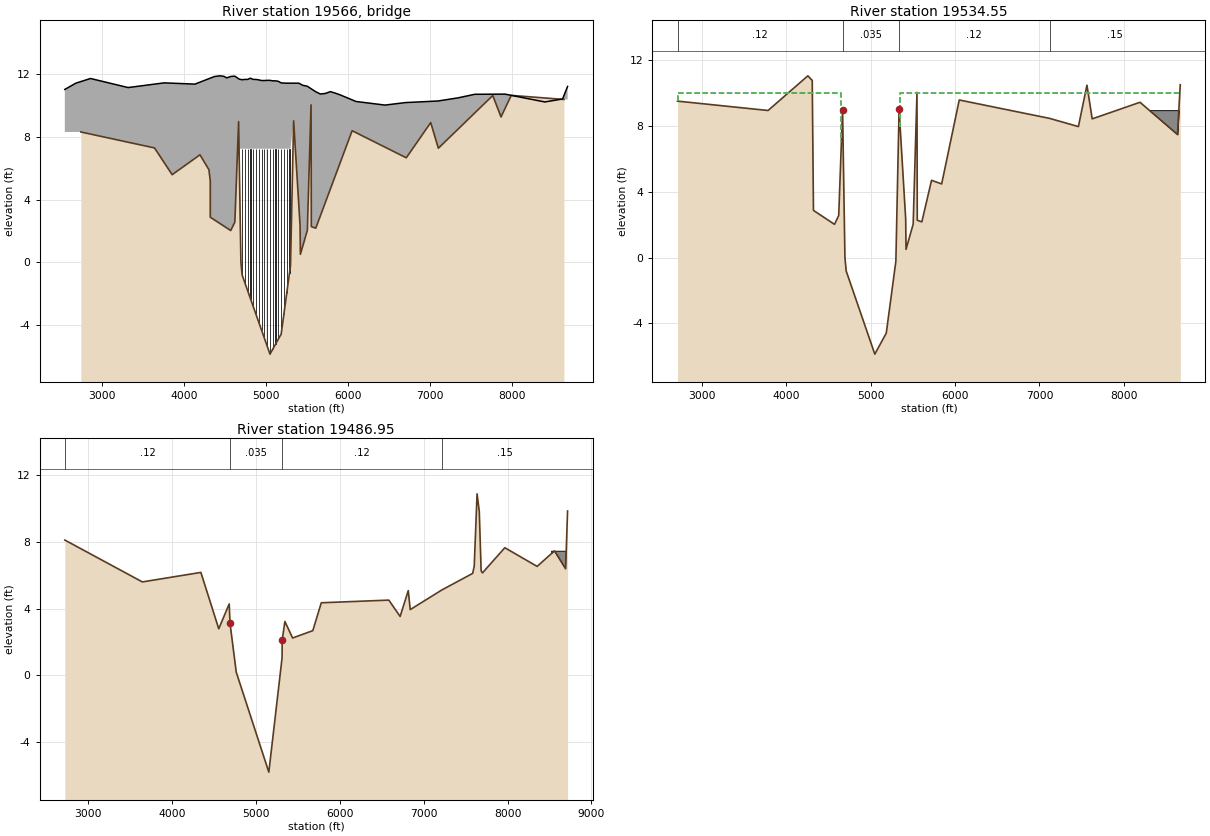
Type RM Length L Ch R = 3 ,19566   ,,,
BEGIN DESCRIPTION:
PORT RD
END DESCRIPTION:
Bridge Culvert--1,0,-1,-1, 0
Deck Dist Width WeirC Skew NumUp NumDn MinLoCord MaxHiCord MaxSubmerge Is_Ogee
20,35,2.6,0, 52, 52, , , .95, 0, 0,0,,
    2548    2682    2861    3319    3758    4133    4368 4431.97 4484.42 4521.23
 4570.64 4618.56 4672.25 4706.65 4740.26 4774.56 4808.61 4842.18 4876.15 4910.44
 4943.93 4978.23 5012.13 5046.31 5079.84 5114.12    5148 5181.97 5215.83 5249.92
 5283.96    5350 5398.48 5448.36  5500.1 5602.37 5659.08 5719.68 5782.93 5844.98
    5903    6095    6448    6698    7092    7337    7541    7911    8142    8395
    8611    8672
   11.04   11.44   11.74   11.16   11.46   11.38   11.86   11.91   11.88   11.78
   11.87   11.89    11.7   11.66   11.68   11.68   11.76   11.68   11.68   11.65
   11.61   11.61   11.62   11.62   11.59   11.59   11.56   11.46   11.45   11.44
   11.44   11.44   11.44    11.3   11.25    10.9   10.75   10.78    10.9    10.8
   10.69   10.27   10.04    10.2    10.3    10.5   10.73   10.74    10.5   10.24
   10.43   11.23
                                                                                
                    7.25    7.25    7.25    7.25    7.25    7.25    7.25    7.25
    7.25    7.25    7.25    7.25    7.25    7.25    7.25    7.25    7.25    7.25
    7.25    7.25
                                                                                
                
    2548    2682    2861    3319    3758    4133    4368 4431.97 4484.42 4521.23
 4570.64 4618.56 4672.25 4706.65 4740.26 4774.56 4808.61 4842.18 4876.15 4910.44
 4943.93 4978.23 5012.13 5046.31 5079.84 5114.12    5148 5181.97 5215.83 5249.92
 5283.96    5350 5398.48 5448.36  5500.1 5602.37 5659.08 5719.68 5782.93 5844.98
    5903    6095    6448    6698    7092    7337    7541    7911    8142    8395
    8611    8672
   11.04   11.44   11.74   11.16   11.46   11.38   11.86   11.91   11.88   11.78
   11.87   11.89    11.7   11.66   11.68   11.68   11.76   11.68   11.68   11.65
   11.61   11.61   11.62   11.62   11.59   11.59   11.56   11.46   11.45   11.44
   11.44   11.44   11.44    11.3   11.25    10.9   10.75   10.78    10.9    10.8
   10.69   10.27   10.04    10.2    10.3    10.5   10.73   10.74    10.5   10.24
   10.43   11.23
                                                                                
                    7.25    7.25    7.25    7.25    7.25    7.25    7.25    7.25
    7.25    7.25    7.25    7.25    7.25    7.25    7.25    7.25    7.25    7.25
    7.25    7.25
                                                                                
                
Pier Skew, UpSta & Num, DnSta & Num=  ,4708, 4 ,4708, 4 , 3 , 3 , 0 ,,
     1.4     1.4    2.25    2.25
      -5    4.85    4.85    7.25
     1.4     1.4    2.25    2.25
      -5    4.85    4.85    7.25
Pier Skew, UpSta & Num, DnSta & Num=  ,4742, 4 ,4742, 4 , 3 , 3 , 0 ,,
     1.4     1.4    2.25    2.25
      -5    4.85    4.85    7.25
     1.4     1.4    2.25    2.25
      -5    4.85    4.85    7.25
Pier Skew, UpSta & Num, DnSta & Num=  ,4776, 4 ,4776, 4 , 3 , 3 , 0 ,,
     1.4     1.4    2.25    2.25
      -5    4.85    4.85    7.25
     1.4     1.4    2.25    2.25
      -5    4.85    4.85    7.25
Pier Skew, UpSta & Num, DnSta & Num=  ,4810, 4 ,4810, 4 , 3 , 3 , 0 ,,
     1.4     1.4    2.25    2.25
      -5    4.85    4.85    7.25
     1.4     1.4    2.25    2.25
      -5    4.85    4.85    7.25
Pier Skew, UpSta & Num, DnSta & Num=  ,4845, 4 ,4845, 4 , 3 , 3 , 0 ,,
     1.4     1.4    2.25    2.25
      -5    4.85    4.85    7.25
     1.4     1.4    2.25    2.25
      -5    4.85    4.85    7.25
Pier Skew, UpSta & Num, DnSta & Num=  ,4877, 4 ,4877, 4 , 3 , 3 , 0 ,,
     1.4     1.4    2.25    2.25
      -5    4.85    4.85    7.25
     1.4     1.4    2.25    2.25
      -5    4.85    4.85    7.25
Pier Skew, UpSta & Num, DnSta & Num=  ,4912, 4 ,4912, 4 , 3 , 3 , 0 ,,
     1.4     1.4    2.25    2.25
      -5    4.85    4.85    7.25
     1.4     1.4    2.25    2.25
      -5    4.85    4.85    7.25
Pier Skew, UpSta & Num, DnSta & Num=  ,4946, 4 ,4946, 4 , 3 , 3 , 0 ,,
     1.4     1.4    2.25    2.25
      -5    4.85    4.85    7.25
     1.4     1.4    2.25    2.25
      -5    4.85    4.85    7.25
Pier Skew, UpSta & Num, DnSta & Num=  ,4979, 4 ,4979, 4 , 3 , 3 , 0 ,,
     1.4     1.4    2.25    2.25
      -5    4.85    4.85    7.25
     1.4     1.4    2.25    2.25
      -5    4.85    4.85    7.25
Pier Skew, UpSta & Num, DnSta & Num=  ,5014, 4 ,5014, 4 , 3 , 3 , 0 ,,
     1.4     1.4    2.25    2.25
      -5    4.85    4.85    7.25
     1.4     1.4    2.25    2.25
      -5    4.85    4.85    7.25
Pier Skew, UpSta & Num, DnSta & Num=  ,5047, 4 ,5047, 4 , 3 , 3 , 0 ,,
     1.4     1.4    2.25    2.25
      -5    4.85    4.85    7.25
     1.4     1.4    2.25    2.25
      -5    4.85    4.85    7.25
Pier Skew, UpSta & Num, DnSta & Num=  ,5081, 4 ,5081, 4 , 3 , 3 , 0 ,,
     1.4     1.4    2.25    2.25
      -5    4.85    4.85    7.25
     1.4     1.4    2.25    2.25
      -5    4.85    4.85    7.25
Pier Skew, UpSta & Num, DnSta & Num=  ,5115, 4 ,5115, 4 , 3 , 3 , 0 ,,
     1.4     1.4    2.25    2.25
      -5    4.85    4.85    7.25
     1.4     1.4    2.25    2.25
      -5    4.85    4.85    7.25
Pier Skew, UpSta & Num, DnSta & Num=  ,5149, 4 ,5149, 4 , 3 , 3 , 0 ,,
     1.4     1.4    2.25    2.25
      -5    4.85    4.85    7.25
     1.4     1.4    2.25    2.25
      -5    4.85    4.85    7.25
Pier Skew, UpSta & Num, DnSta & Num=  ,5183, 4 ,5183, 4 , 3 , 3 , 0 ,,
     1.4     1.4    2.25    2.25
      -5    4.85   4.851   7.251
     1.4     1.4    2.25    2.25
      -5    4.85   4.851   7.251
Pier Skew, UpSta & Num, DnSta & Num=  ,5217, 4 ,5217, 4 , 3 , 3 , 0 ,,
     1.4     1.4    2.25    2.25
      -5    4.85   4.851   7.251
     1.4     1.4    2.25    2.25
      -5    4.85   4.851   7.251
Pier Skew, UpSta & Num, DnSta & Num=  ,5251, 4 ,5251, 4 , 3 , 3 , 0 ,,
     1.4     1.4    2.25    2.25
      -5    4.85   4.851   7.251
     1.4     1.4    2.25    2.25
      -5    4.85   4.851   7.251
Pier Skew, UpSta & Num, DnSta & Num=  ,5285, 4 ,5285, 4 , 3 , 3 , 0 ,,
     1.4     1.4    2.25    2.25
      -5    4.85   4.851   7.251
     1.4     1.4    2.25    2.25
      -5    4.85   4.851   7.251
BR Coef=-1 , 1 , 0 ,1.25, 0 ,,,.8,0,2,0,
WSPro=,,,, 1 ,,,, 0 ,,,, 0 ,,,,-1 ,-1 ,-1 , 0 , 0 , 0 , 0 , 0
BC Design=,, 0 ,, 0 ,,,,,,

Type RM Length L Ch R = 1 ,19534.55,57.92,47.6,43.73
XS GIS Cut Line= 6
     3228512.696    13788407.597     3227062.339    13788344.774
     3225871.816    13788551.082     3225149.877    13788758.962
     3224675.967    13789199.273     3223771.293    13790864.593
#Sta/Elev= 30
 2707.59    9.52 3781.37    8.95 4253.45   11.06 4305.32   10.78 4319.82    2.87
 4569.25    2.02 4619.36    2.56 4664.92    8.98 4692.99     .01 4707.95    -.82
 5047.34   -5.88 5183.38    -4.6 5297.06    -.22 5335.08    9.03 5413.61    2.34
 5417.44      .5 5502.28    2.03 5547.37   10.05 5550.82    2.27  5604.9    2.17
 5720.23     4.7 5840.11    4.48 6048.63    9.59 7119.51    8.47 7461.58    7.97
 7562.86   10.49 7625.16    8.44 8192.41    9.45 8636.04    7.49 8669.65   10.52
#Mann= 4 ,-1 , 0
 2707.59     .12       0 4664.92    .035       0 5335.08     .12       0
 7119.51     .15       0
#XS Ineff= 2 , 0
       0    4651      10    5348       0      10
Permanent Ineff=
       F       F
#Block Obstruct= 1 ,-1
  8302.7 8660.17    8.97
Bank Sta=4664.92,5335.08
XS Rating Curve= 0
Exp/Cntr=.5,.3

Type RM Length L Ch R = 1 ,19486.95,22.25,22.09,20
XS GIS Cut Line= 6
     3228508.171    13788362.828     3226890.785    13788313.318
     3225271.907     13788651.91     3224925.512    13788863.724
     3224619.449    13789209.732     3223748.789    13790842.089
#Sta/Elev= 30
 2718.41    8.11 3643.48     5.6 4341.37    6.17 4554.46    2.79  4679.2    4.28
 4688.94    3.12 4763.26     .19 5151.75    -5.8 5309.62    1.05 5311.06    2.12
 5343.37    3.23 5435.31    2.24 5676.28    2.68 5777.54    4.35 6583.02    4.51
 6717.54    3.53 6814.76    5.08 6838.06    3.94 7215.64    5.12 7582.78    6.11
  7601.4    6.54 7635.29   10.88 7661.65    9.83 7683.87    6.27  7699.3    6.14
 7966.55    7.65 8351.79    6.53 8558.76    7.46 8691.18    6.39 8714.72    9.85
#Mann= 4 ,-1 , 0
 2718.41     .12       0 4688.94    .035       0 5311.06     .12       0
 7215.64     .15       0
#Block Obstruct= 2 ,-1
  8413.8 8420.47    6.56  8524.4 8778.92    7.44
Bank Sta=4688.94,5311.06
XS Rating Curve= 0
Exp/Cntr=.5,.3