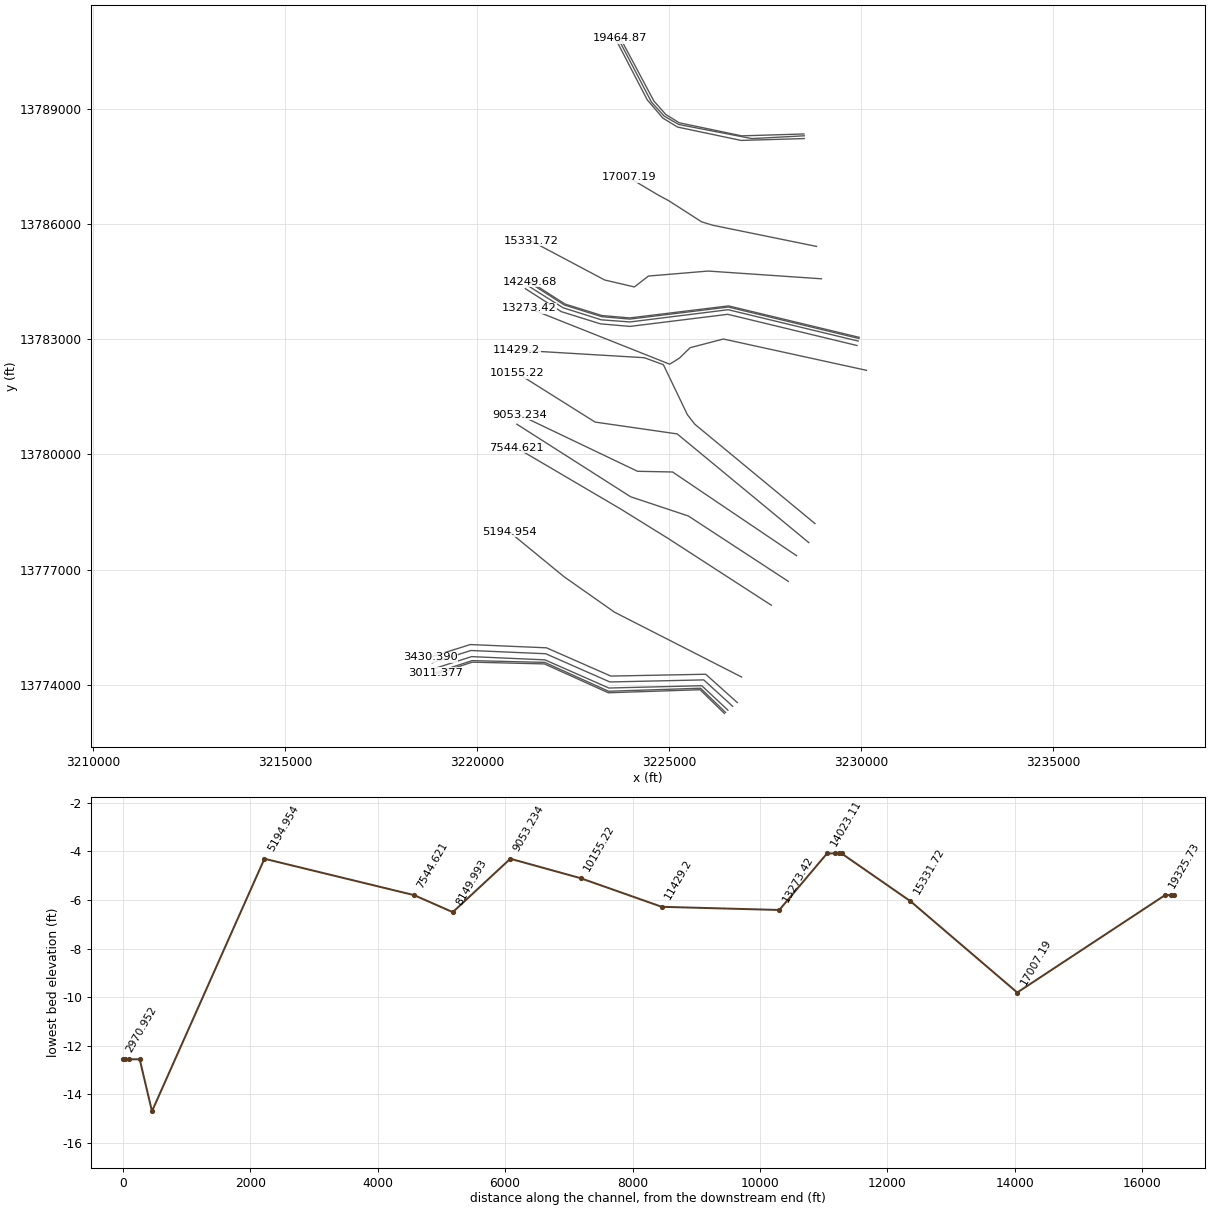
HEC-RAS study A104_00_00.prj: A104-00-00

--- A104_00_00.g01 (geometry) --- (continued)

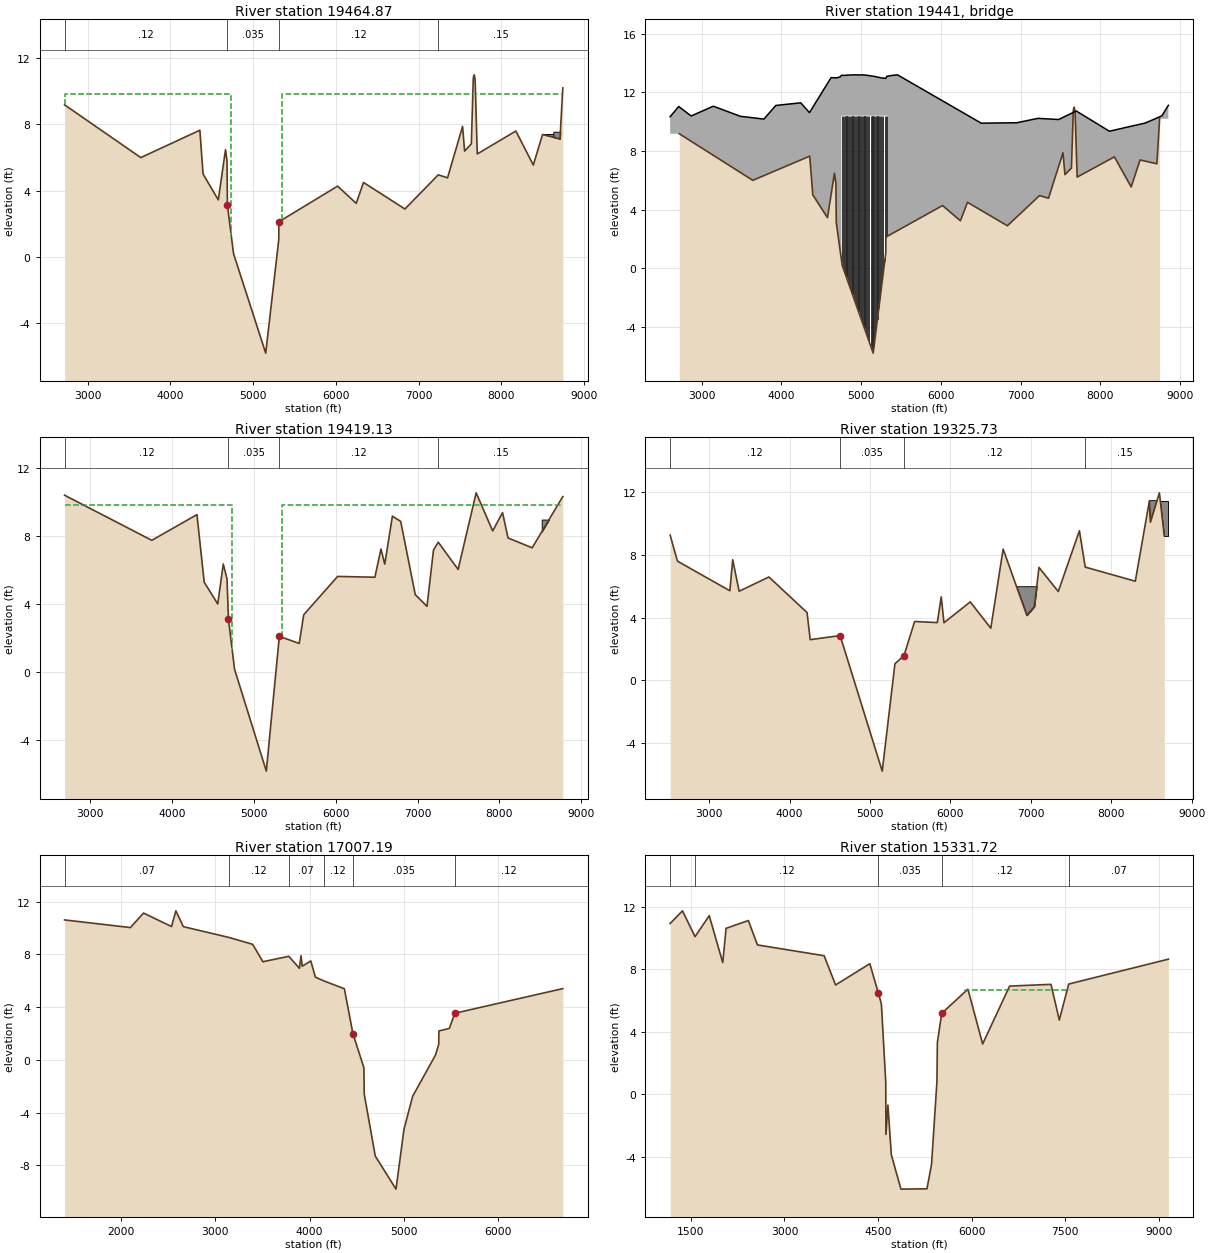
Type RM Length L Ch R = 1 ,19464.87,52.9,45.74,60.42
XS GIS Cut Line= 6
     3228509.286    13788342.859     3226888.166     13788293.47
     3225264.142    13788633.382     3224912.609    13788848.369
     3224601.322     13789200.64     3223730.785    13790833.087
#Sta/Elev= 30
 2721.62    9.17 3642.66    5.99 4356.19    7.64 4394.83       5 4578.86    3.44
 4666.06    6.47 4683.98    5.79 4688.94    3.12 4763.26     .19 5151.75    -5.8
 5309.62    1.05 5311.06    2.12 6020.64    4.27 6244.77    3.23 6333.53    4.49
 6833.84    2.89 7236.26    4.95 7348.68    4.77  7530.3    7.87 7554.66    6.38
 7636.07    6.82 7659.67   10.79 7671.04   10.98 7681.88   10.67 7707.74    6.21
 8174.11    7.59 8384.91    5.54 8496.17    7.38 8707.15    7.12 8741.14   10.19
#Mann= 4 ,-1 , 0
 2721.62     .12       0 4688.94    .035       0 5311.06     .12       0
 7236.26     .15       0
#XS Ineff= 2 , 0
       0    4738    9.85    5349       0    9.85
Permanent Ineff=
       F       F
#Block Obstruct= 2 ,-1
 8494.74 8850.25    7.38  8626.6 8737.78    7.55
Bank Sta=4688.94,5311.06
XS Rating Curve= 0
Exp/Cntr=.5,.3

Type RM Length L Ch R = 3 ,19441   ,,,
BEGIN DESCRIPTION:
RAILROAD DS OF PORT RD
END DESCRIPTION:
Bridge Culvert--1,0,-1,-1, 0
Deck Dist Width WeirC Skew NumUp NumDn MinLoCord MaxHiCord MaxSubmerge Is_Ogee
10,30,2.6,0, 41, 41, , , .95, 0, 0,0,,
    2607    2714    2870    3147    3487    3782    3931    4244    4353    4624
 4691.65 4742.72 4752.65 4795.38 4844.81 4878.27 4927.57 4977.07  5021.2  5072.8
 5118.34 5159.28 5202.33    5236 5282.39    5311 5322.91    5335 5375.94    5456
    6506    6642    6952    7217    7475    7697    8112    8318    8562    8769
    8851
   10.33   11.03   10.38   11.05   10.36   10.17    11.1   11.28   10.61      13
   12.98   13.06   13.16   13.15   13.18   13.18   13.19   13.18   13.19   13.16
   13.12   13.09   13.04      13   12.96   12.95   13.09    13.1   13.14   13.19
    9.89     9.9    9.92   10.22   10.14   10.72    9.34     9.6     9.9   10.39
   11.11
                                                                                
                    10.4    10.4    10.4    10.4    10.4    10.4    10.4    10.4
    10.4    10.4    10.4    10.4    10.4    10.4    10.4    10.4
                                                                                
        
    2607    2714    2870    3147    3487    3782    3931    4244    4353    4624
 4691.65 4742.72 4752.65 4795.38 4844.81 4878.27 4927.57 4977.07  5021.2  5072.8
 5118.34 5159.28 5202.33    5236 5282.39    5311 5322.91    5335 5375.94    5456
    6506    6642    6952    7217    7475    7697    8112    8318    8562    8769
    8851
   10.33   11.03   10.38   11.05   10.36   10.17    11.1   11.28   10.61      13
   12.98   13.06   13.16   13.15   13.18   13.18   13.19   13.18   13.19   13.16
   13.12   13.09   13.04      13   12.96   12.95   13.09    13.1   13.14   13.19
    9.89     9.9    9.92   10.22   10.14   10.72    9.34     9.6     9.9   10.39
   11.11
                                                                                
                    10.4    10.4    10.4    10.4    10.4    10.4    10.4    10.4
    10.4    10.4    10.4    10.4    10.4    10.4    10.4    10.4
                                                                                
        
Pier Skew, UpSta & Num, DnSta & Num=  ,4758, 2 ,4758, 2 , 0 , 0 , 0 ,,
     1.5     1.5
      -6    10.4
     1.5     1.5
      -6    10.4
Pier Skew, UpSta & Num, DnSta & Num=  ,4772, 2 ,4772, 2 , 0 , 0 , 0 ,,
     1.5     1.5
      -6    10.4
     1.5     1.5
      -6    10.4
Pier Skew, UpSta & Num, DnSta & Num=  ,4787, 2 ,4787, 2 , 0 , 0 , 0 ,,
     1.5     1.5
      -6    10.4
     1.5     1.5
      -6    10.4
Pier Skew, UpSta & Num, DnSta & Num=  ,4802, 2 ,4802, 2 , 0 , 0 , 0 ,,
     1.5     1.5
      -6    10.4
     1.5     1.5
      -6    10.4
Pier Skew, UpSta & Num, DnSta & Num=  ,4817, 2 ,4817, 2 , 0 , 0 , 0 ,,
     1.5     1.5
      -6    10.4
     1.5     1.5
      -6    10.4
Pier Skew, UpSta & Num, DnSta & Num=  ,4832, 2 ,4832, 2 , 0 , 0 , 0 ,,
     1.5     1.5
      -6    10.4
     1.5     1.5
      -6    10.4
Pier Skew, UpSta & Num, DnSta & Num=  ,4847, 2 ,4847, 2 , 0 , 0 , 0 ,,
     1.5     1.5
      -6    10.4
     1.5     1.5
      -6    10.4
Pier Skew, UpSta & Num, DnSta & Num=  ,4863, 2 ,4863, 2 , 0 , 0 , 0 ,,
     1.5     1.5
      -6    10.4
     1.5     1.5
      -6    10.4
Pier Skew, UpSta & Num, DnSta & Num=  ,4877, 2 ,4877, 2 , 0 , 0 , 0 ,,
     1.5     1.5
      -6    10.4
     1.5     1.5
      -6    10.4
Pier Skew, UpSta & Num, DnSta & Num=  ,4892, 2 ,4892, 2 , 0 , 0 , 0 ,,
     1.5     1.5
      -6    10.4
     1.5     1.5
      -6    10.4
Pier Skew, UpSta & Num, DnSta & Num=  ,4907, 2 ,4907, 2 , 0 , 0 , 0 ,,
     1.5     1.5
      -6    10.4
     1.5     1.5
      -6    10.4
Pier Skew, UpSta & Num, DnSta & Num=  ,4923, 2 ,4923, 2 , 0 , 0 , 0 ,,
     1.5     1.5
      -6    10.4
     1.5     1.5
      -6    10.4
Pier Skew, UpSta & Num, DnSta & Num=  ,4937, 2 ,4937, 2 , 0 , 0 , 0 ,,
     1.5     1.5
      -6    10.4
     1.5     1.5
      -6    10.4
Pier Skew, UpSta & Num, DnSta & Num=  ,4952, 2 ,4952, 2 , 0 , 0 , 0 ,,
     1.5     1.5
      -6    10.4
     1.5     1.5
      -6    10.4
Pier Skew, UpSta & Num, DnSta & Num=  ,4967, 2 ,4967, 2 , 0 , 0 , 0 ,,
     1.5     1.5
      -6    10.4
     1.5     1.5
      -6    10.4
Pier Skew, UpSta & Num, DnSta & Num=  ,4982, 2 ,4982, 2 , 0 , 0 , 0 ,,
     1.5     1.5
      -6    10.4
     1.5     1.5
      -6    10.4
Pier Skew, UpSta & Num, DnSta & Num=  ,4997, 2 ,4997, 2 , 0 , 0 , 0 ,,
     1.5     1.5
      -6    10.4
     1.5     1.5
      -6    10.4
Pier Skew, UpSta & Num, DnSta & Num=  ,5013, 2 ,5013, 2 , 0 , 0 , 0 ,,
     1.5     1.5
      -6    10.4
     1.5     1.5
      -6    10.4
Pier Skew, UpSta & Num, DnSta & Num=  ,5027, 2 ,5027, 2 , 0 , 0 , 0 ,,
     1.5     1.5
      -6    10.4
     1.5     1.5
      -6    10.4
Pier Skew, UpSta & Num, DnSta & Num=  ,5042, 2 ,5042, 2 , 0 , 0 , 0 ,,
     1.5     1.5
      -6    10.4
     1.5     1.5
      -6    10.4
Pier Skew, UpSta & Num, DnSta & Num=  ,5057, 2 ,5057, 2 , 0 , 0 , 0 ,,
     1.5     1.5
      -6    10.4
     1.5     1.5
      -6    10.4
Pier Skew, UpSta & Num, DnSta & Num=  ,5072, 2 ,5072, 2 , 0 , 0 , 0 ,,
     1.5     1.5
      -6    10.4
     1.5     1.5
      -6    10.4
Pier Skew, UpSta & Num, DnSta & Num=  ,5087, 2 ,5087, 2 , 0 , 0 , 0 ,,
     1.5     1.5
      -6    10.4
     1.5     1.5
      -6    10.4
Pier Skew, UpSta & Num, DnSta & Num=  ,5102, 2 ,5102, 2 , 0 , 0 , 0 ,,
     1.5     1.5
      -6    10.4
     1.5     1.5
      -6    10.4
Pier Skew, UpSta & Num, DnSta & Num=  ,5122, 2 ,5122, 2 , 0 , 0 , 0 ,,
       4       4
      -6    10.4
       4       4
      -6    10.4
Pier Skew, UpSta & Num, DnSta & Num=  ,5142, 2 ,5142, 2 , 0 , 0 , 0 ,,
       4       4
      -6    10.4
       4       4
      -6    10.4
Pier Skew, UpSta & Num, DnSta & Num=  ,5162, 2 ,5162, 2 , 0 , 0 , 0 ,,
     1.5     1.5
      -6    10.4
     1.5     1.5
      -6    10.4
Pier Skew, UpSta & Num, DnSta & Num=  ,5177, 2 ,5177, 2 , 0 , 0 , 0 ,,
     1.5     1.5
      -6    10.4
     1.5     1.5
      -6    10.4
Pier Skew, UpSta & Num, DnSta & Num=  ,5192, 2 ,5192, 2 , 0 , 0 , 0 ,,
     1.5     1.5
      -6    10.4
     1.5     1.5
      -6    10.4
Pier Skew, UpSta & Num, DnSta & Num=  ,5206, 2 ,5206, 2 , 0 , 0 , 0 ,,
     1.5     1.5
      -6    10.4
     1.5     1.5
      -6    10.4
Pier Skew, UpSta & Num, DnSta & Num=  ,5222, 2 ,5222, 2 , 0 , 0 , 0 ,,
     1.5     1.5
      -6    10.4
     1.5     1.5
      -6    10.4
Pier Skew, UpSta & Num, DnSta & Num=  ,5237, 2 ,5237, 2 , 0 , 0 , 0 ,,
     1.5     1.5
      -6    10.4
     1.5     1.5
      -6    10.4
Pier Skew, UpSta & Num, DnSta & Num=  ,5250, 2 ,5250, 2 , 0 , 0 , 0 ,,
     1.5     1.5
      -6    10.4
     1.5     1.5
      -6    10.4
Pier Skew, UpSta & Num, DnSta & Num=  ,5266, 2 ,5266, 2 , 0 , 0 , 0 ,,
     1.5     1.5
      -6    10.4
     1.5     1.5
      -6    10.4
Pier Skew, UpSta & Num, DnSta & Num=  ,5280, 2 ,5280, 2 , 0 , 0 , 0 ,,
     1.5     1.5
      -6    10.4
     1.5     1.5
      -6    10.4
Pier Skew, UpSta & Num, DnSta & Num=  ,5296, 2 ,5296, 2 , 0 , 0 , 0 ,,
     1.5     1.5
      -6    10.4
     1.5     1.5
      -6    10.4
Pier Skew, UpSta & Num, DnSta & Num=  ,5311, 2 ,5311, 2 , 0 , 0 , 0 ,,
     1.5     1.5
      -6    10.4
     1.5     1.5
      -6    10.4
Pier Skew, UpSta & Num, DnSta & Num=  ,5327, 2 ,5327, 2 , 0 , 0 , 0 ,,
     1.5     1.5
      -6    10.4
     1.5     1.5
      -6    10.4
BR Coef=-1 , 1 , 0 ,1.25, 0 ,,,.8,0,2,0,
WSPro=,,,, 1 ,,,, 0 ,,,, 0 ,,,,-1 ,-1 ,-1 , 0 , 0 , 0 , 0 , 0
BC Design=,, 0 ,, 0 ,,,,,,

Type RM Length L Ch R = 1 ,19419.13,80.6,93.4,59.59
XS GIS Cut Line= 6
     3228516.689    13788295.006     3227153.029    13788222.121
     3225250.958    13788588.899     3224869.504    13788807.698
     3224540.941    13789167.767     3223681.276    13790810.583
#Sta/Elev= 30
 2685.64   10.41 3751.97    7.76  4303.8    9.27 4392.45     5.3 4558.08    4.02
 4625.61    6.37 4671.35    5.49 4688.94    3.12 4763.26     .19 5151.75    -5.8
 5311.06    2.12 5553.86     1.7 5609.22    3.39 6024.03    5.64 6479.03    5.59
 6552.99    7.25 6599.73    6.36 6693.02    9.18  6794.4    8.87 6972.54    4.57
  7115.9    3.88  7195.6    7.19 7253.46    7.65 7496.34    6.05 7716.92   10.55
 7919.18    8.31 8039.32    9.39 8106.42     7.9 8401.71    7.32 8776.07   10.33
#Mann= 4 ,-1 , 0
 2685.64     .12       0 4688.94    .035       0 5311.06     .12       0
 7253.46     .15       0
#XS Ineff= 2 , 0
       0    4738    9.85    5349       0    9.85
Permanent Ineff=
       F       F
#Block Obstruct= 1 ,-1
 8518.28 8628.27    8.98
Bank Sta=4688.94,5311.06
XS Rating Curve= 0
Exp/Cntr=.5,.3

Type RM Length L Ch R = 1 ,19325.73,2667.82,2318.53,2060.44
XS GIS Cut Line= 6
     3228515.973    13788223.045     3226872.456    13788174.383
     3225217.553    13788522.211     3224835.194     13788756.24
      3224427.97    13789231.549     3223631.766    13790765.574
#Sta/Elev= 30
 2514.57    9.26 2605.55     7.6 3257.23    5.71 3292.26    7.69 3372.63    5.68
  3742.7    6.59 4216.89    4.32 4256.34    2.59    4628    2.85 5151.75    -5.8
 5309.62    1.05    5422    1.57 5554.64    3.75 5836.55    3.68 5885.32    5.32
 5919.34    3.67 6246.41       5 6501.56    3.32 6655.02    8.37 6949.88    4.14
 7043.15     4.7 7100.89     7.2 7340.72    5.66 7603.45    9.54 7675.92    7.22
 8298.57    6.32 8473.07   11.43 8486.65   10.09 8597.82   11.96 8659.03    9.23
#Mann= 4 ,-1 , 0
 2514.57     .12       0    4628    .035       0    5422     .12       0
 7675.92     .15       0
#Block Obstruct= 2 ,-1
 8472.63 8709.67   11.46    6800    7100       6
Bank Sta=4628,5422
XS Rating Curve= 0
Exp/Cntr=.3,.1

Type RM Length L Ch R = 1 ,17007.19,1258.87,1675.47,3087.92
XS GIS Cut Line= 6
     3228837.159    13785414.115     3226143.187    13785963.905
     3225845.848    13786053.484     3224985.311     13786606.41
     3224713.732    13786751.938     3223944.025    13787210.097
#Sta/Elev= 30
 1399.72   10.61 2098.37   10.03 2237.37   11.13 2534.74   10.11 2580.77    11.3
 2659.59    10.1 3144.35    9.28 3395.53    8.76 3504.16    7.44 3778.76    7.85
 3891.88    6.94 3908.22    7.89 3921.25     7.1 4012.23     7.5 4061.17    6.27
 4148.84    5.99 4368.46    5.39 4459.95    1.97 4575.75     -.6 4579.35    -2.6
 4696.41    -7.3  4916.6   -9.81 5001.49   -5.26 5093.13   -2.77 5334.72     .35
  5369.8    1.17 5372.16    2.19 5482.83    2.38 5540.05    3.53 6686.48     5.4
#Mann= 6 ,-1 , 0
 1399.72     .07       0 3144.35     .12       0 3778.76     .07       0
 4148.84     .12       0 4459.95    .035       0 5540.05     .12       0
Bank Sta=4459.95,5540.05
XS Rating Curve= 0
Exp/Cntr=.3,.1

Type RM Length L Ch R = 1 ,15331.72,1024.65,1082.04,1488.84
XS GIS Cut Line= 6
     3228965.443    13784571.103     3226014.902    13784772.693
     3224459.845    13784642.728     3224093.131    13784358.778
     3223319.811    13784539.789     3221396.664    13785560.726
#Sta/Elev= 30
 1168.43   10.93 1366.03   11.74 1567.55   10.09 1794.71   11.43 2011.16    8.43
 2064.79   10.62  2421.2   11.12 2567.28    9.56 3635.75    8.87 3818.64       7
 4367.76    8.36  4503.4    6.49 4552.88    5.79 4623.11     .75  4625.1   -2.55
 4657.46    -.68  4712.4   -3.86 4866.34   -6.05  5282.8   -6.03  5356.7   -4.46
 5443.01     .84 5449.65    3.32    5520    5.19  5939.4    6.73 6175.44    3.23
 6606.96    6.93 7269.88    7.04 7403.49    4.76 7554.38    7.06 9150.87    8.65
#Mann= 5 ,-1 , 0
 1168.43     .07       0 1567.55     .12       0  4503.4    .035       0
    5520     .12       0 7554.38     .07       0
#XS Ineff= 1 ,-1
 5899.88    7576    6.69
Permanent Ineff=
       F
Bank Sta=4503.4,5520
XS Rating Curve= 0
Exp/Cntr=.3,.1

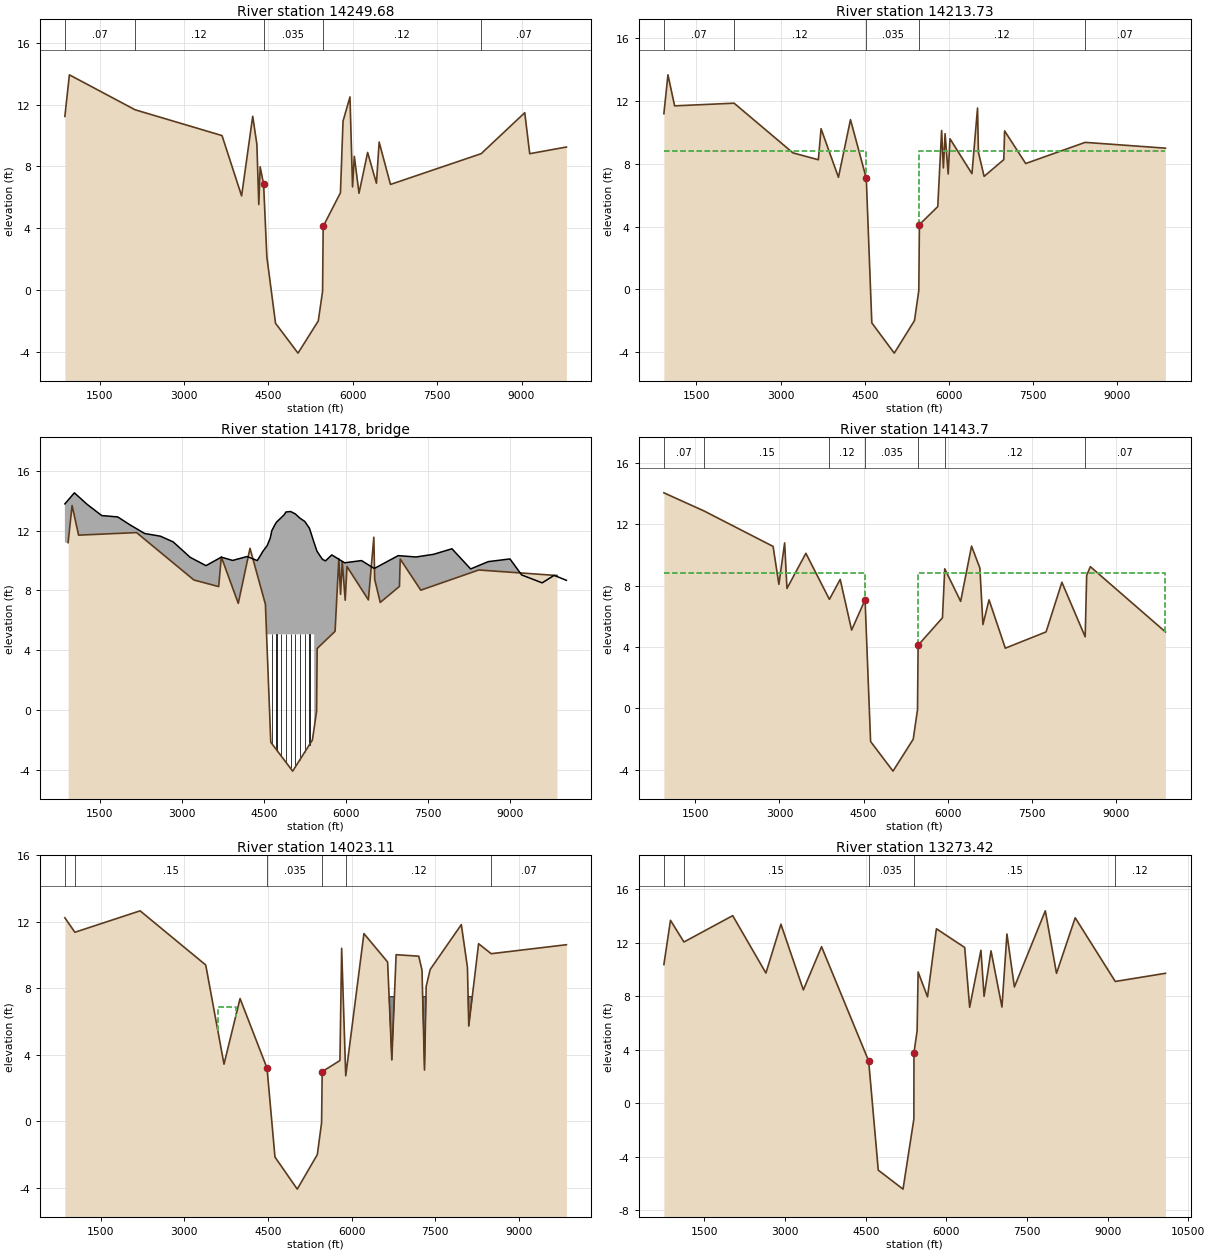
Type RM Length L Ch R = 1 ,14249.68,32.33,35.95,30.01
XS GIS Cut Line= 6
     3229947.675    13783046.292     3226544.773    13783865.368
     3223973.732    13783551.842     3223248.121    13783614.416
     3222284.883    13783914.596     3221384.229    13784490.977
#Sta/Elev= 30
  879.15   11.23  959.56   13.92 2127.89   11.66 3674.07    9.99 4022.21    6.09
 4219.94   11.24 4293.85    9.43 4327.89    5.53 4352.12    7.97    4414    6.83
    4471    2.16 4625.68   -2.15 5025.44   -4.08 5385.83      -2 5462.35    -.08
 5472.95    4.12    5780    6.29 5825.76   10.92 5949.46   12.49 5995.06    6.67
 6026.91    8.65 6110.06    6.26 6263.65     8.9 6419.99    6.91 6468.32    9.57
  6669.7    6.83 8282.41    8.82 9057.77   11.47 9145.93    8.82 9798.73    9.25
#Mann= 5 ,-1 , 0
  879.15     .07       0 2127.89     .12       0    4414    .035       0
 5472.95     .12       0 8282.41     .07       0
Bank Sta=4414,5472.95
XS Rating Curve= 0
Exp/Cntr=.5,.3

Type RM Length L Ch R = 1 ,14213.73,75.43,70.03,75.31
XS GIS Cut Line= 6
      3229939.97    13783017.298     3226542.048    13783835.491
     3223974.484    13783521.779     3223242.987    13783584.839
     3222271.861    13783887.527     3221366.528    13784466.756
#Sta/Elev= 30
  923.41    11.2  995.84   13.68 1114.76    11.7 2173.63   11.87  3221.3     8.7
 3673.83    8.26 3721.99   10.24 4031.68    7.14 4245.95   10.82 4527.05    7.08
 4625.68   -2.15 5025.44   -4.08 5385.83      -2 5462.35    -.08 5472.95    4.12
  5799.9    5.27 5868.41   10.13 5899.94    7.74 5930.25    9.92 5985.43    7.35
 6017.52     9.6 6408.64    7.37 6508.09   11.56 6523.71    8.74 6624.95     7.2
 6975.72    8.27 6990.24    10.1 7365.72    8.02  8424.7    9.37 9853.52       9
#Mann= 5 ,-1 , 0
  923.41     .07       0 2173.63     .12       0 4527.05    .035       0
 5472.95     .12       0  8424.7     .07       0
#XS Ineff= 2 , 0
       0    4520    8.85    5474       0    8.85
Permanent Ineff=
       F       F
Bank Sta=4527.05,5472.95
XS Rating Curve= 0
Exp/Cntr=.5,.3

Type RM Length L Ch R = 3 ,14178   ,,,
BEGIN DESCRIPTION:
RED BLUFF RD
END DESCRIPTION:
Bridge Culvert--1,0,-1,-1, 0
Deck Dist Width WeirC Skew NumUp NumDn MinLoCord MaxHiCord MaxSubmerge Is_Ogee
17,50,2.6,0, 50, 50, , , .95, 0, 0,0,,
     864    1038    1264    1537    1829    2053    2322    2609    2842    3152
    3442    3722    3929    4192    4378    4432 4477.45 4559.26 4615.21  4644.3
 4701.78 4729.98 4815.95 4874.04 4901.96 4988.07    5074 5159.92 5245.77    5332
 5417.83 5469.28 5521.12 5569.64    5625    5740    5974    6283    6516    6953
    7278    7601    7935    8276    8598    8995    9208    9583    9801   10026
   13.79   14.53   13.78   13.01   12.92   12.39   11.81   11.63   11.25   10.22
    9.66   10.23   10.01   10.27      10   10.31    10.6      11    11.5      12
    12.4   12.57   12.87   13.08   13.25   13.28   13.12   12.83   12.62   12.16
   11.18   10.63   10.34   10.08    9.98   10.38    9.85      10    9.47   10.33
   10.24   10.42   10.79    9.44    9.93   10.11    9.04    8.51    9.01    8.68
                                                                                
                                            5.07    5.07    5.07    5.07    5.07
    5.07    5.07    5.07    5.07    5.07    5.07    5.07    5.07    5.07    5.07
    5.07
                                                                                
     864    1038    1264    1537    1829    2053    2322    2609    2842    3152
    3442    3722    3929    4192    4378    4432 4477.45 4559.26 4615.21  4644.3
 4701.78 4729.98 4815.95 4874.04 4901.96 4988.07    5074 5159.92 5245.77    5332
 5417.83 5469.28 5521.12 5569.64    5625    5740    5974    6283    6516    6953
    7278    7601    7935    8276    8598    8995    9208    9583    9801   10026
   13.79   14.53   13.78   13.01   12.92   12.39   11.81   11.63   11.25   10.22
    9.66   10.23   10.01   10.27      10   10.31    10.6      11    11.5      12
    12.4   12.57   12.87   13.08   13.25   13.28   13.12   12.83   12.62   12.16
   11.18   10.63   10.34   10.08    9.98   10.38    9.85      10    9.47   10.33
   10.24   10.42   10.79    9.44    9.93   10.11    9.04    8.51    9.01    8.68
                                                                                
                                            5.07    5.07    5.07    5.07    5.07
    5.07    5.07    5.07    5.07    5.07    5.07    5.07    5.07    5.07    5.07
    5.07
                                                                                
Pier Skew, UpSta & Num, DnSta & Num=  ,4644, 4 ,4644, 4 , 3 , 3 , 0 ,,
       2       2     2.5     2.5
      -9    2.56    2.57    5.07
       2       2     2.5     2.5
      -9    2.56    2.57    5.07
Pier Skew, UpSta & Num, DnSta & Num=  ,4730, 4 ,4730, 4 , 3 , 3 , 0 ,,
       2       2     2.5     2.5
      -9    2.56    2.57    5.07
       2       2     2.5     2.5
      -9    2.56    2.57    5.07
Pier Skew, UpSta & Num, DnSta & Num=  ,4816, 4 ,4816, 4 , 3 , 3 , 0 ,,
       2       2     2.5     2.5
      -9    2.56    2.57    5.07
       2       2     2.5     2.5
      -9    2.56    2.57    5.07
Pier Skew, UpSta & Num, DnSta & Num=  ,4902, 4 ,4902, 4 , 3 , 3 , 0 ,,
       2       2     2.5     2.5
      -9    2.56    2.57    5.07
       2       2     2.5     2.5
      -9    2.56    2.57    5.07
Pier Skew, UpSta & Num, DnSta & Num=  ,4988, 4 ,4988, 4 , 3 , 3 , 0 ,,
       2       2     2.5     2.5
      -9    2.56    2.57    5.07
       2       2     2.5     2.5
      -9    2.56    2.57    5.07
Pier Skew, UpSta & Num, DnSta & Num=  ,5074, 4 ,5074, 4 , 3 , 3 , 0 ,,
       2       2     2.5     2.5
      -9    2.56    2.57    5.07
       2       2     2.5     2.5
      -9    2.56    2.57    5.07
Pier Skew, UpSta & Num, DnSta & Num=  ,5160, 4 ,5160, 4 , 3 , 3 , 0 ,,
       2       2     2.5     2.5
      -9    2.56    2.57    5.07
       2       2     2.5     2.5
      -9    2.56    2.57    5.07
Pier Skew, UpSta & Num, DnSta & Num=  ,5246, 4 ,5246, 4 , 3 , 3 , 0 ,,
       2       2     2.5     2.5
      -9    2.56    2.57    5.07
       2       2     2.5     2.5
      -9    2.56    2.57    5.07
Pier Skew, UpSta & Num, DnSta & Num=  ,5332, 4 ,5332, 4 , 3 , 3 , 0 ,,
       2       2     2.5     2.5
      -9    2.56    2.57    5.07
       2       2     2.5     2.5
      -9    2.56    2.57    5.07
BR Coef=-1 , 1 , 0 ,1.25, 0 ,,,.8,0,2,0,
WSPro=,,,, 1 ,,,, 0 ,,,, 0 ,,,,-1 ,-1 ,-1 , 0 , 0 , 0 , 0 , 0
BC Design=,, 0 ,, 0 ,,,,,,

Type RM Length L Ch R = 1 ,14143.7 ,129.32,120.58,114.73
XS GIS Cut Line= 6
     3229921.993    13782949.646     3226535.689    13783765.778
     3223979.665     13783447.17      3223230.62     13783502.95
     3222234.549    13783817.708     3221334.101    13784383.476
#Sta/Elev= 30
   939.5   14.05 1655.01   12.87 2886.85   10.56 2990.36    8.09 3093.07   10.79
 3134.17    7.82 3471.78   10.11 3890.96    7.11  4083.6    8.41 4287.41    5.11
 4527.05    7.08 4625.68   -2.15 5025.44   -4.08 5385.83      -2 5462.35    -.08
 5472.95    4.12 5907.17    5.91 5948.04     9.1 6231.45    6.98 6426.12   10.58
 6574.34    9.15 6629.04    5.47 6737.84    7.08 7027.96    3.93  7755.1    4.99
 8037.06    8.22 8452.31    4.67 8478.79    8.67 8544.53    9.24 9883.33    4.99
#Mann= 7 ,-1 , 0
   939.5     .07       0 1655.01     .15       0 3890.96     .12       0
 4527.05    .035       0 5472.95     .15       0 5948.04     .12       0
 8452.31     .07       0
#XS Ineff= 2 , 0
       0    4520    8.85    5474       0    8.85
Permanent Ineff=
       F       F
Bank Sta=4527.05,5472.95
XS Rating Curve= 0
Exp/Cntr=.5,.3

Type RM Length L Ch R = 1 ,14023.11,797.08,749.69,650.66
XS GIS Cut Line= 6
     3229891.174    13782833.671     3226524.787     13783646.27
     3223979.249    13783331.379     3223210.471    13783397.514
     3222189.388    13783716.091     3221254.425    13784313.351
#Sta/Elev= 30
  855.14   12.25 1035.16   11.38 2205.45   12.67 3383.33    9.41 3710.86    3.44
 3999.09    7.39 4483.24     3.2 4625.68   -2.15 5025.44   -4.08 5385.83      -2
 5462.35    -.08 5472.95    2.99 5791.42    3.66 5822.34   10.41 5895.58    2.74
 6222.07    11.3 6647.18    9.59 6722.52     3.7 6799.72   10.03 7205.67    9.94
 7263.98    9.11 7309.11    3.09 7339.21    8.12 7411.15    9.14 7970.08   11.84
 8079.63    9.27 8103.45    5.74 8279.74   10.69 8505.81   10.09 9855.93   10.63
#Mann= 6 ,-1 , 0
  855.14     .07       0 1035.16     .15       0 4483.24    .035       0
 5472.95     .15       0 5895.58     .12       0 8505.81     .07       0
#XS Ineff= 1 ,-1
    3600    3920     6.9
Permanent Ineff=
       F
#Block Obstruct= 1 ,-1
    6570    8300     7.5
Bank Sta=4483.24,5472.95
XS Rating Curve= 0
Exp/Cntr=.3,.1

Type RM Length L Ch R = 1 ,13273.42,3740.38,1844.22,283.09
XS GIS Cut Line= 6
     3230136.953    13782187.642     3226410.836     13783002.83
     3225546.516    13782777.456     3225268.612    13782506.878
     3225013.224     13782347.26     3221357.977    13783799.781
#Sta/Elev= 30
  745.16   10.37  867.95   13.68 1118.39   12.06 2025.64   14.03 2643.44    9.74
 2922.76   13.39 3339.77    8.48 3678.54   11.71    4555    3.17  4733.5   -4.99
 5194.17   -6.41 5396.01   -1.17 5397.41    3.78 5456.38    5.42 5475.03    9.82
 5649.74    7.96 5815.06   13.05 6341.87   11.65 6433.76    7.18 6643.76   11.44
 6701.98       8  6831.4    11.4 7034.68     7.2  7127.3   12.66 7266.23     8.7
 7841.36   14.39 8049.56    9.72 8397.34   13.87 9142.88    9.1110075.96    9.72
#Mann= 5 ,-1 , 0
  745.16     .07       0 1118.39     .15       0    4555    .035       0
 5397.41     .15       0 9142.88     .12       0
Bank Sta=4555,5397.41
XS Rating Curve= 0
Exp/Cntr=.3,.1

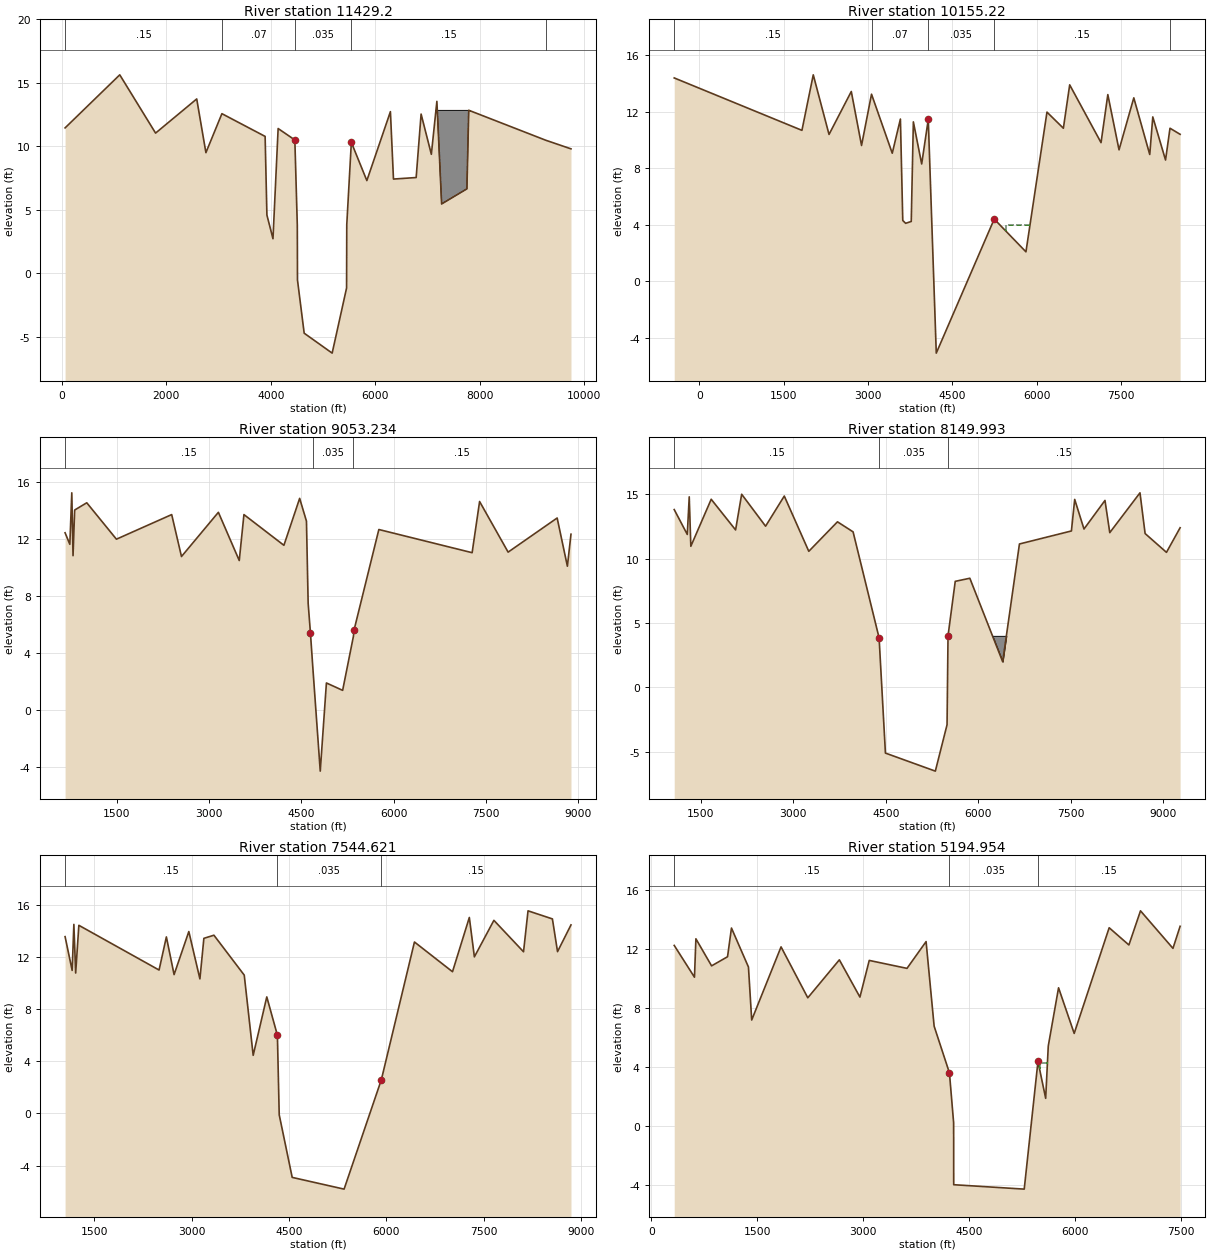
Type RM Length L Ch R = 1 ,11429.2 ,452.38,1273.99,951.18
XS GIS Cut Line= 6
     3228796.164    13778197.199     3225667.657    13780783.006
     3225474.357    13781031.525     3224848.667    13782334.375
      3224350.08    13782516.399     3221026.169     13782714.25
#Sta/Elev= 30
   63.18   11.46 1109.24   15.64 1794.77   11.05 2581.87   13.74 2757.88    9.51
 3063.99   12.58  3890.8   10.79 3924.93     4.6 4041.15    2.73  4139.8   11.41
 4459.48   10.51 4506.51    3.79    4510    -.52  4638.2   -4.71 5173.55   -6.28
 5449.48   -1.15    5453    3.83 5540.52   10.32 5837.35    7.31  6288.2   12.74
 6346.69    7.43 6780.81    7.55 6875.36   12.55  7071.4    9.38 7177.27   13.55
 7268.02    5.47    7752    6.66 7787.04   12.85 9259.22   10.49 9743.22    9.81
#Mann= 5 ,-1 , 0
   63.18     .15       0 3063.99     .07       0 4459.48    .035       0
 5540.52     .15       0 9259.22     .12       0
#XS Ineff= 1 ,-1
    3895    4120       9
Permanent Ineff=
       F
#Block Obstruct= 1 ,-1
 7151.37 7818.83   12.84
Bank Sta=4459.48,5540.52
XS Rating Curve= 0
Exp/Cntr=.3,.1

Type RM Length L Ch R = 1 ,10155.22,1184.39,1101.99,841.48
XS GIS Cut Line= 4
      3228635.63    13777700.824     3225207.598     13780531.84
     3223069.892    13780839.978     3221047.738    13782111.046
#Sta/Elev= 30
 -445.96   14.38 1824.63   10.67 2026.02    14.6 2306.43   10.38  2702.1   13.42
 2884.38     9.6 3061.76   13.23 3430.32    9.05 3575.37   11.47 3617.24    4.29
 3668.57    4.09 3767.96    4.22 3805.64   11.27 3953.58    8.29 4070.52   11.44
    4213    -5.1 5243.38    4.39  5807.2    2.07 6181.07   11.96 6472.66   10.82
 6584.95   13.89 7142.27     9.8 7262.93    13.2 7462.13    9.29 7724.67   12.97
 8008.27    8.96 8062.37   11.62 8288.97    8.57 8368.32   10.82  8548.2   10.39
#Mann= 5 ,-1 , 0
 -445.96     .15       0 3061.76     .07       0 4070.52    .035       0
 5243.38     .15       0 8368.32     .12       0
#XS Ineff= 2 ,-1
    5450    5870       4    3570    3800      10
Permanent Ineff=
       F       F
Bank Sta=4070.52,5243.38
XS Rating Curve= 0
Exp/Cntr=.3,.1

Type RM Length L Ch R = 1 ,9053.234,864.14,903.24,756.96
XS GIS Cut Line= 4
     3228317.356    13777359.744     3225087.991    13779540.022
     3224175.742    13779558.267     3221101.459    13781026.989
#Sta/Elev= 30
  661.96   12.46  739.09   11.65  770.84   15.27  791.14   10.85  817.51   14.06
 1014.08   14.57  1495.7   12.01 2393.32   13.74 2552.31   10.79 3151.66    13.9
 3490.56   10.51 3566.65   13.74 4215.76   11.58 4471.54   14.88 4581.93   13.28
 4609.58     7.5 4646.72    5.41  4687.8    2.84    4806    -4.3    4906     1.9
 5169.64    1.38 5345.08    5.19 5353.29    5.59  5757.7   12.69 7272.64   11.06
 7393.77   14.66 7857.14    11.1  8653.4    13.5  8819.5   10.11 8877.96   12.36
#Mann= 3 ,-1 , 0
  661.96     .15       0  4687.8    .035       0 5345.08     .15       0
Bank Sta=4646.72,5353.29
XS Rating Curve= 0
Exp/Cntr=.3,.1

Type RM Length L Ch R = 1 ,8149.993,825.58,605.37,492.89
XS GIS Cut Line= 4
     3228102.978    13776691.128     3225498.032    13778394.361
     3223995.179    13778895.313     3221032.411    13780784.614
#Sta/Elev= 30
 1067.22    13.8 1279.26   11.87  1310.9   14.79 1336.87   10.95 1667.39    14.6
 2063.25   12.22  2161.8   14.99 2549.92   12.51 2853.53   14.85  3251.3   10.56
 3716.58   12.85 3970.12   12.07  4392.3    3.84    4495    -5.1    5305    -6.5
    5495    -2.9 5510.93       4 5627.96    8.23 5864.84    8.47 6398.04    1.99
 6669.87   11.13 7513.35   12.14 7566.72   14.59 7717.43   12.29 8058.21   14.51
 8136.01   12.01  8626.2    15.1 8709.35   11.94 9056.04   10.48 9277.61   12.39
#Mann= 3 ,-1 , 0
 1067.22     .15       0  4392.3    .035       0 5510.93     .15       0
#Block Obstruct= 1 ,-1
    6157    6509       4
Bank Sta=4392.3,5510.93
XS Rating Curve= 0
Exp/Cntr=.3,.1

Type RM Length L Ch R = 1 ,7544.621,2298.49,2349.67,2696.58
XS GIS Cut Line= 4
       3227658.6    13776071.138     3224973.826    13777808.345
     3223727.027     13778581.36     3221025.628    13780168.951
#Sta/Elev= 30
 1050.24   13.56 1159.35   10.97 1185.59    14.5 1213.35   10.77 1262.53   14.43
 2499.03      11 2611.56   13.54 2730.58   10.65 2957.62   13.95  3128.5   10.32
 3189.61   13.43 3344.55   13.67 3811.93   10.61 3949.73    4.46 4159.47    8.94
    4323       6    4351     -.1    4551    -4.9    5351    -5.8    5926     2.6
  6435.6   13.15 7022.14   10.87 7281.45   15.03  7359.4   12.01 7660.16   14.81
 8116.94    12.4 8186.35   15.54 8562.08   14.92 8641.09   12.41 8848.39   14.46
#Mann= 3 ,-1 , 0
 1050.24     .15       0    4323    .035       0    5926     .15       0
Bank Sta=4323,5926
XS Rating Curve= 0
Exp/Cntr=.3,.1

Type RM Length L Ch R = 1 ,5194.954,1613.75,1764.56,2675.4
XS GIS Cut Line= 4
     3226885.585    13774200.939     3223577.411    13775888.274
     3222264.115    13776810.905     3220834.452    13777982.897
#Sta/Elev= 30
  323.35   12.26  610.31    10.1  630.45   12.71  852.71   10.87 1078.67   11.49
 1134.43   13.44 1375.08   10.79 1421.04    7.19 1836.94   12.16 2215.78     8.7
 2662.86   11.28 2954.35    8.75  3086.4   11.24 3621.09    10.7 3891.61   12.52
 4005.76    6.77 4222.43     3.6    4282      .2    4283      -4    5282    -4.3
 5476.87    4.38 5585.95    1.87 5622.61    5.42 5768.34    9.38 5989.97    6.28
 6485.48   13.46 6765.03   12.29 6929.34   14.61 7389.32   12.06 7490.63   13.56
#Mann= 3 ,-1 , 0
  323.35     .15       0 4222.43    .035       0 5476.87     .15       0
#XS Ineff= 1 ,-1
    5500    5610    4.25
Permanent Ineff=
       F
Bank Sta=4222.43,5476.87
XS Rating Curve= 0
Exp/Cntr=.3,.1

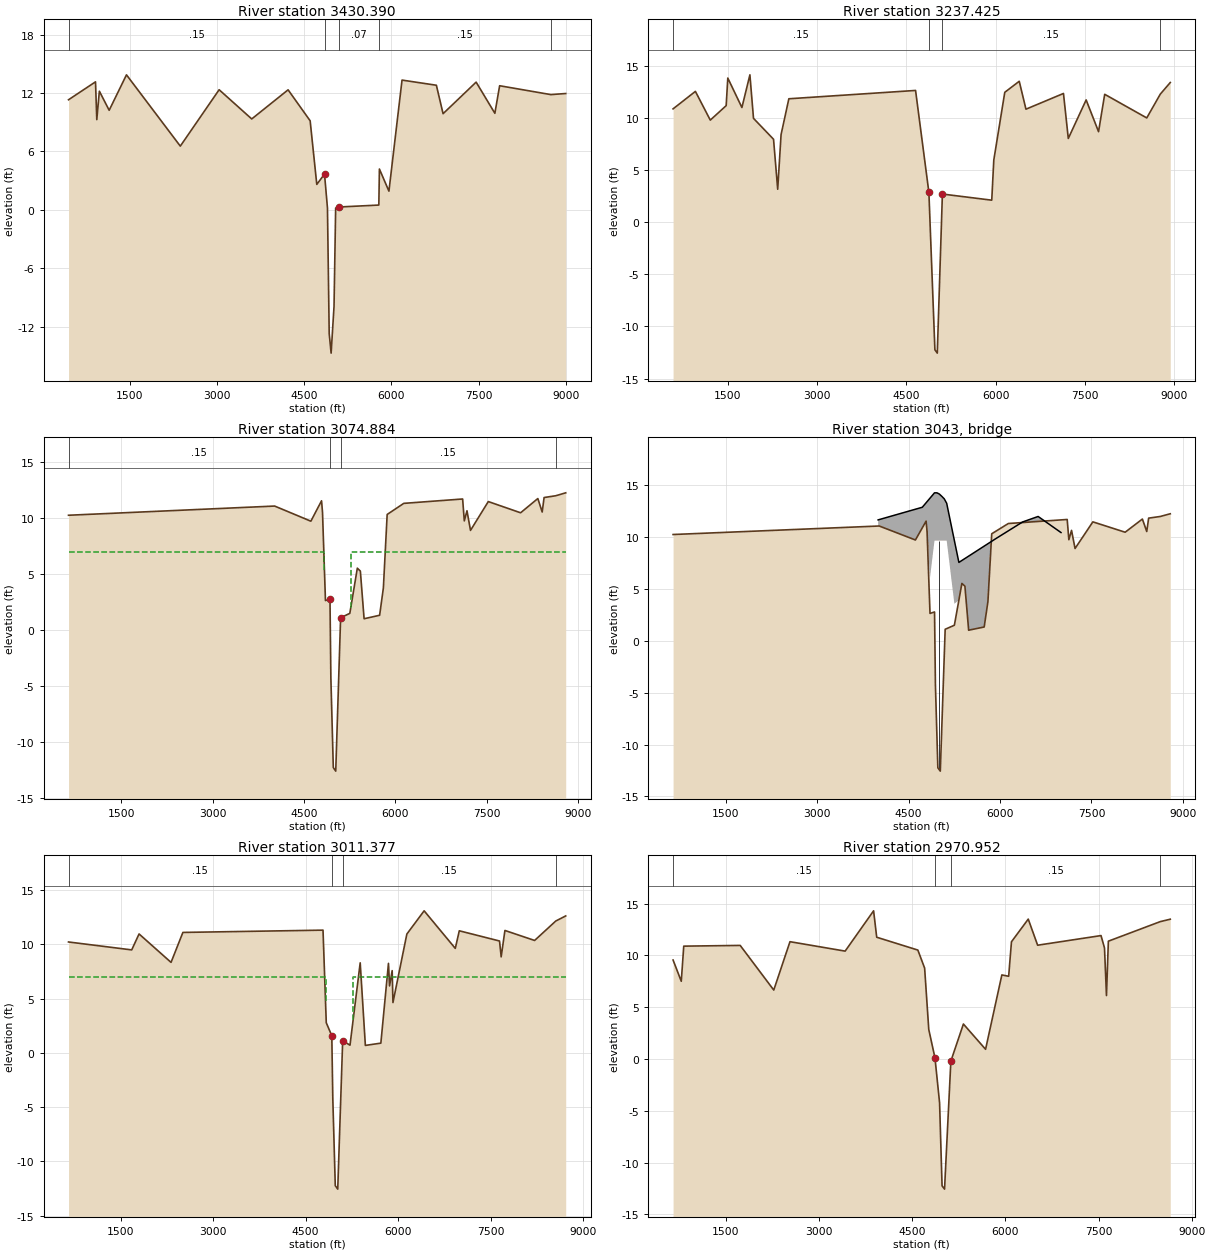
Type RM Length L Ch R = 1 ,3430.390,165.2,192.97,156.49
XS GIS Cut Line= 6
     3226772.999    13773536.564     3225950.631    13774272.829
     3223479.874    13774225.448     3221803.708    13774961.374
      3219819.93    13775046.186     3218774.364    13774716.459
#Sta/Elev= 30
  448.99   11.31  912.78   13.15  935.01    9.27  979.15   12.19  1147.8   10.23
 1445.23   13.87 2370.48    6.55 3037.88   12.34 3598.34    9.34 4223.23   12.33
 4602.51    9.15 4716.54    2.62 4849.41    3.68    4900      .2    4930   -12.7
    4963   -14.7    5013    -9.9    5041      .2    5093      .3    5783      .5
    5793     4.2 5956.65    1.93 6181.79   13.33 6772.25    12.8 6887.38    9.88
 7455.65   13.12 7777.68    9.92 7859.65   12.75 8739.09   11.84 8995.48   11.95
#Mann= 5 ,-1 , 0
  448.99     .15       0 4849.41    .035       0    5093     .07       0
    5793     .15       0 8739.09      .1       0
Bank Sta=4849.41,5093
XS Rating Curve= 0
Exp/Cntr=.3,.1

Type RM Length L Ch R = 1 ,3237.425,167.62,162.54,160.05
XS GIS Cut Line= 6
     3226652.856    13773438.632     3225899.944    13774125.991
     3223454.892    13774072.174     3221784.344    13774806.964
     3219836.972    13774891.655     3218827.334    13774570.791
#Sta/Elev= 30
  580.56    10.9   955.6   12.58 1205.73    9.82  1472.7   11.21 1500.08   13.86
 1737.14   11.03 1871.47   14.17 1931.88    9.99 2268.68    7.98 2338.47    3.18
  2395.2    8.43 2525.93   11.87 4655.07   12.67 4879.01    2.88    4980  -12.24
    5020  -12.56 5105.88    2.72 5935.18    2.13 5969.62    5.98 6154.08   12.49
 6397.18   13.55 6509.96   10.87 7140.46   12.38 7221.47    8.06 7521.43   11.76
 7729.78    8.71 7833.23    12.3 8539.79   10.03 8767.82   12.32  8934.9   13.43
#Mann= 4 ,-1 , 0
  580.56     .15       0 4879.01    .035       0 5105.88     .15       0
 8767.82      .1       0
Bank Sta=4879.01,5105.88
XS Rating Curve= 0
Exp/Cntr=.5,.3

Type RM Length L Ch R = 1 ,3074.884,84.53,63.51,105.46
XS GIS Cut Line= 6
     3226528.838    13773337.541     3225847.622    13773974.418
     3223429.103    13773913.955     3221764.356    13774647.572
     3219854.563    13774732.139     3218882.013    13774420.424
#Sta/Elev= 30
  636.55   10.26 4017.84   11.08 4612.05    9.73 4787.18   11.55 4803.24   10.51
 4851.23    2.65 4925.57    2.79    4940   -4.22    4980  -12.24    5020  -12.56
    5100    1.12 5250.95    1.51 5374.22    5.54 5423.82    5.28 5485.16    1.03
 5739.92    1.34 5801.48    3.78 5863.68   10.33 6136.14   11.32 7101.64   11.71
 7128.99    9.76 7172.98   10.66 7230.74    8.91 7522.62   11.48 8052.45   10.48
 8335.16   11.75 8406.74   10.55 8437.89   11.84 8629.42      12 8792.54   12.26
#Mann= 4 ,-1 , 0
  636.55     .15       0 4925.57    .035       0    5100     .15       0
 8629.42      .1       0
#XS Ineff= 2 , 0
       0    4835       7    5266       0       7
Permanent Ineff=
       F       F
Bank Sta=4925.57,5100
XS Rating Curve= 0
Exp/Cntr=.5,.3

Type RM Length L Ch R = 3 ,3043    ,,,
BEGIN DESCRIPTION:
NASA RD 1
END DESCRIPTION:
Bridge Culvert--1,0,-1,-1, 0
Deck Dist Width WeirC Skew NumUp NumDn MinLoCord MaxHiCord MaxSubmerge Is_Ogee
9,50,2.6,0, 13, 13, , , .95, 0, 0,0,,
    4000    4725    4925    4965    5005    5045    5085    5125    5325    5930
    6370    6625    7000
   11.67   12.89   14.28   14.28   14.16   13.94    13.7   13.27    7.57    9.86
   11.47      12   10.45
       0       0    9.67    9.67    9.67    9.67    9.67    9.67       0       0
       0       0
    4000    4725    4925    4965    5005    5045    5085    5125    5325    5930
    6370    6625    7000
   11.67   12.89   14.28   14.28   14.16   13.94    13.7   13.27    7.57    9.86
   11.47      12   10.45
       0       0    9.67    9.67    9.67    9.67    9.67    9.67       0       0
       0       0
Pier Skew, UpSta & Num, DnSta & Num=  ,5000, 2 ,5000, 2 , 0 , 0 , 0 ,,
     6.5     6.5
     -13      12
     6.5     6.5
     -13      12
BR Coef=-1 , 1 , 0 ,, 0 ,,,.8,-1,2,0,
WSPro=,,,, 1 ,,,, 0 ,,,, 0 ,,,,-1 ,-1 ,-1 , 0 , 0 , 0 , 0 , 0
BC Design=,, 0 ,, 0 ,,,,,,

Type RM Length L Ch R = 1 ,3011.377,41.63,40.42,40.29
XS GIS Cut Line= 6
     3226467.835    13773278.787     3225817.018    13773908.877
     3223421.017    13773830.116     3221757.537    13774581.741
     3219867.487    13774627.561     3218920.553     13774318.28
#Sta/Elev= 30
  657.05   10.21 1680.86    9.48 1800.26   10.95 2318.56    8.33 2510.57   11.09
 4781.41    11.3 4833.97    2.77 4923.77    1.57    4940   -4.22    4980  -12.24
    5020  -12.56    5100    1.12 5218.61      .7 5383.89    8.29 5467.62     .68
 5718.63     .89 5842.08    8.24 5859.56    6.16  5902.1    7.57 5914.83    4.63
 6140.04   10.94 6420.01   13.08 6924.84    9.62 6989.92   11.24 7641.75    10.3
 7668.56    8.84 7729.44   11.27 8210.48   10.35 8553.33   12.14 8714.47   12.61
#Mann= 4 ,-1 , 0
  657.05     .15       0 4923.77    .035       0    5100     .15       0
 8553.33      .1       0
#XS Ineff= 2 , 0
       0    4822       7    5269       0       7
Permanent Ineff=
       F       F
Bank Sta=4923.77,5100
XS Rating Curve= 0
Exp/Cntr=.5,.3

Type RM Length L Ch R = 1 ,2970.952,1179.41,2970.95,854.12
XS GIS Cut Line= 6
      3226436.46    13773253.966     3225804.355    13773870.119
     3223414.655    13773790.475     3221751.457    13774541.886
     3219871.876    13774587.714     3218935.408    13774281.141
#Sta/Elev= 30
  648.91    9.56  780.87    7.51  820.85    10.9 1729.58   10.97 2270.18    6.66
 2531.21   11.33 3419.52   10.42 3877.57   14.31 3927.87   11.76 4590.49   10.52
 4699.38    8.78 4766.14    2.85    4866     .11    4940   -4.22    4980  -12.24
    5020  -12.56 5121.86     -.2 5323.71    3.38 5680.64     .94 5942.89    8.12
 6052.53    7.99 6097.54   11.32 6367.95   13.51 6518.85   10.99 7539.64   11.92
 7595.41   10.73 7627.37    6.13 7657.85   11.38 8494.49   13.27  8654.6    13.5
#Mann= 4 ,-1 , 0
  648.91     .15       0    4866    .035       0 5121.86     .15       0
 8494.49      .1       0
Bank Sta=4866,5121.86
XS Rating Curve= 0
Exp/Cntr=.3,.1

Chan Stop Cuts=-1

--- A104_00_00.g02 (geometry) ---

Geom Title=A104-00-00 June 2007 (Floodway)
Version=Version 3.0.1  Mar 2001

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
River Reach=A104-00-00    ,A104-00-00_0030